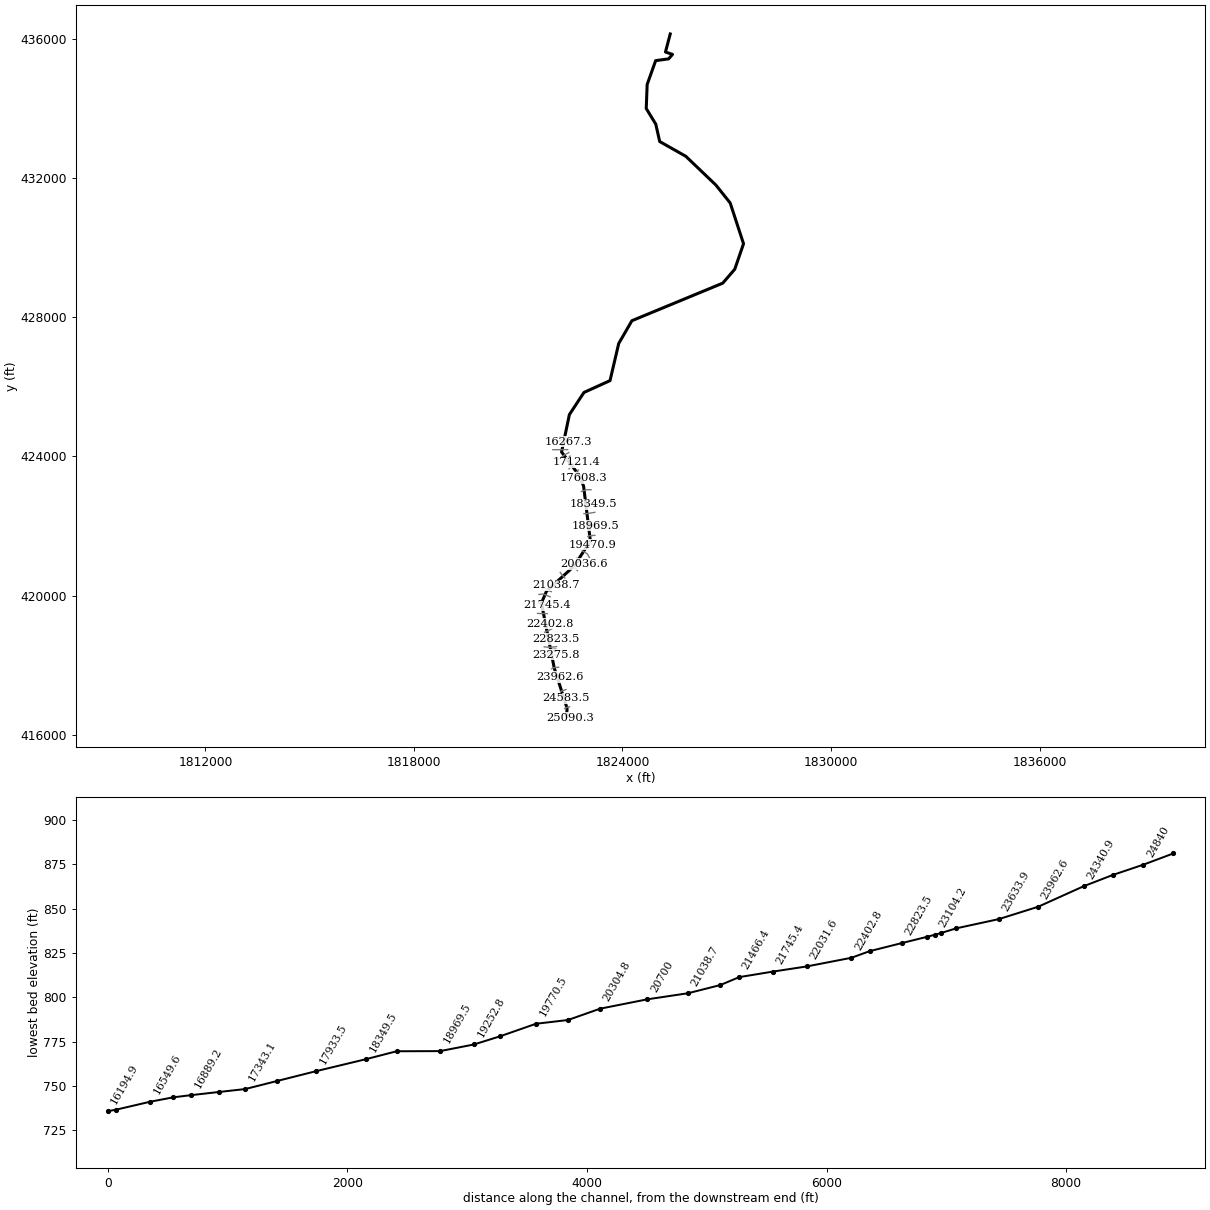
--- SLGHTERCK.prj (project) ---

Proj Title=SLGHTERCK
Current Plan=p01
Default Exp/Contr=0,0
English Units
Geom File=g01
Flow File=f01
Plan File=p01
BEGIN DESCRIPTION:
END DESCRIPTION:
DSS Export Rating Curves= 0
DSS Export Rating Curve Sorted= 0
DSS Export Volume Flow Curves= 0
DXF Filename=..\..\..\..\..\03_EngrWorking\AFG\SLGHTERCK\SLGHTERCK.
DXF OffsetX= 0
DXF OffsetY= 0
DXF ScaleX= 0
DXF ScaleY= 0

--- SLGHTERCK.p01 (plan) ---

Plan Title=Floodplain
Program Version=4.00
Geom File=g01
Flow File=f01
K Sum by GR=0
Std Step Tol=0.01
Critical Tol=0.01
Num of Std Step Trials=20
Max Error Tol=0.3
Flow Tol Ratio=0.001
Split Flow NTrial=30
Split Flow Tol=0.02
Split Flow Ratio=0.02
Log Output Level=0
Friction Slope Method=1
Unsteady Friction Slope Method=2
Unsteady Bridges Friction Slope Method=1
Global Log Level=0
CheckData=False
Run HTab=0
Run UNet=0
Run PostProcess=0
UNET Theta=0
UNET Theta Warmup=0
UNET ZTol=0
UNET ZSATol=0
UNET MxIter=0
UNET MaxInSteps=0
UNET DtIC=0
UNET DtMin=0
UNET MaxCRTS=0
UNET WFStab=0
UNET SFStab=0
UNET WFX=0
UNET SFX=0
UNET DSS MLevel=0
UNET DZMax Abort=0
UNET Convert EG Bridges=0
UNET Use Existing IB Tables=0
UNET Froude Limit=0
UNET Froude Power=0
Write IC File=0
Echo Input=False
Echo Output=False
Write Detailed=0

--- SLGHTERCK.f01 (steady flow) ---

Flow Title=NFF Regression Equation
Program Version=4.10
Number of Profiles= 1
Profile Names=P100yr
River Rch & RM=SLGHTERCK,Main            ,25090.3
860.3117
River Rch & RM=SLGHTERCK,Main            ,22554.4
 1547.88
River Rch & RM=SLGHTERCK,Main            ,18969.5
1851.503
River Rch & RM=SLGHTERCK,Main            ,16549.6
1941.875
River Rch & RM=SLGHTERCK,Main            ,15589.7
2229.656
River Rch & RM=SLGHTERCK,Main            ,10061
2482.498
River Rch & RM=SLGHTERCK,Main            ,7571.1
2645.026
River Rch & RM=SLGHTERCK,Main            ,2124.8
3139.578
Boundary for River Rch & Prof#=SLGHTERCK,Main            , 1
Up Type= 0
Dn Type= 3
Dn Slope=0.03
DSS Import GetInterval= 0
DSS Import GetPeak= 0
DSS Import FillOption= 0

--- SLGHTERCK.g01 (geometry) ---

Geom Title=USGS 10m DEM
Program Version=4.10

River Reach=SLGHTERCK       ,Main
Reach XY= 30
     1822392.073      416528.743     1822406.179      416755.523
     1822035.606      417917.371     1821668.346      419782.442
     1821813.384      420124.316     1822616.162      420854.177
      1823075.19      421575.705     1822881.344      423148.184
     1822754.608      423455.476     1822247.412      424129.177
     1822472.412      425205.566     1822891.761      425842.629
     1823641.162      426182.649     1823891.856      427251.399
     1824271.717      427906.955     1826884.217      428986.816
     1827230.302      429387.768     1827482.829      430121.538
     1827098.482      431294.557     1826686.995      431809.733
     1825821.023       432637.51     1825071.023      433061.121
     1824958.269      433560.962     1824683.523      434011.816
     1824709.912      434702.788     1824954.356      435388.899
     1825327.967      435440.288     1825439.079       435568.76
     1825236.301      435636.816     1825373.685      436156.376

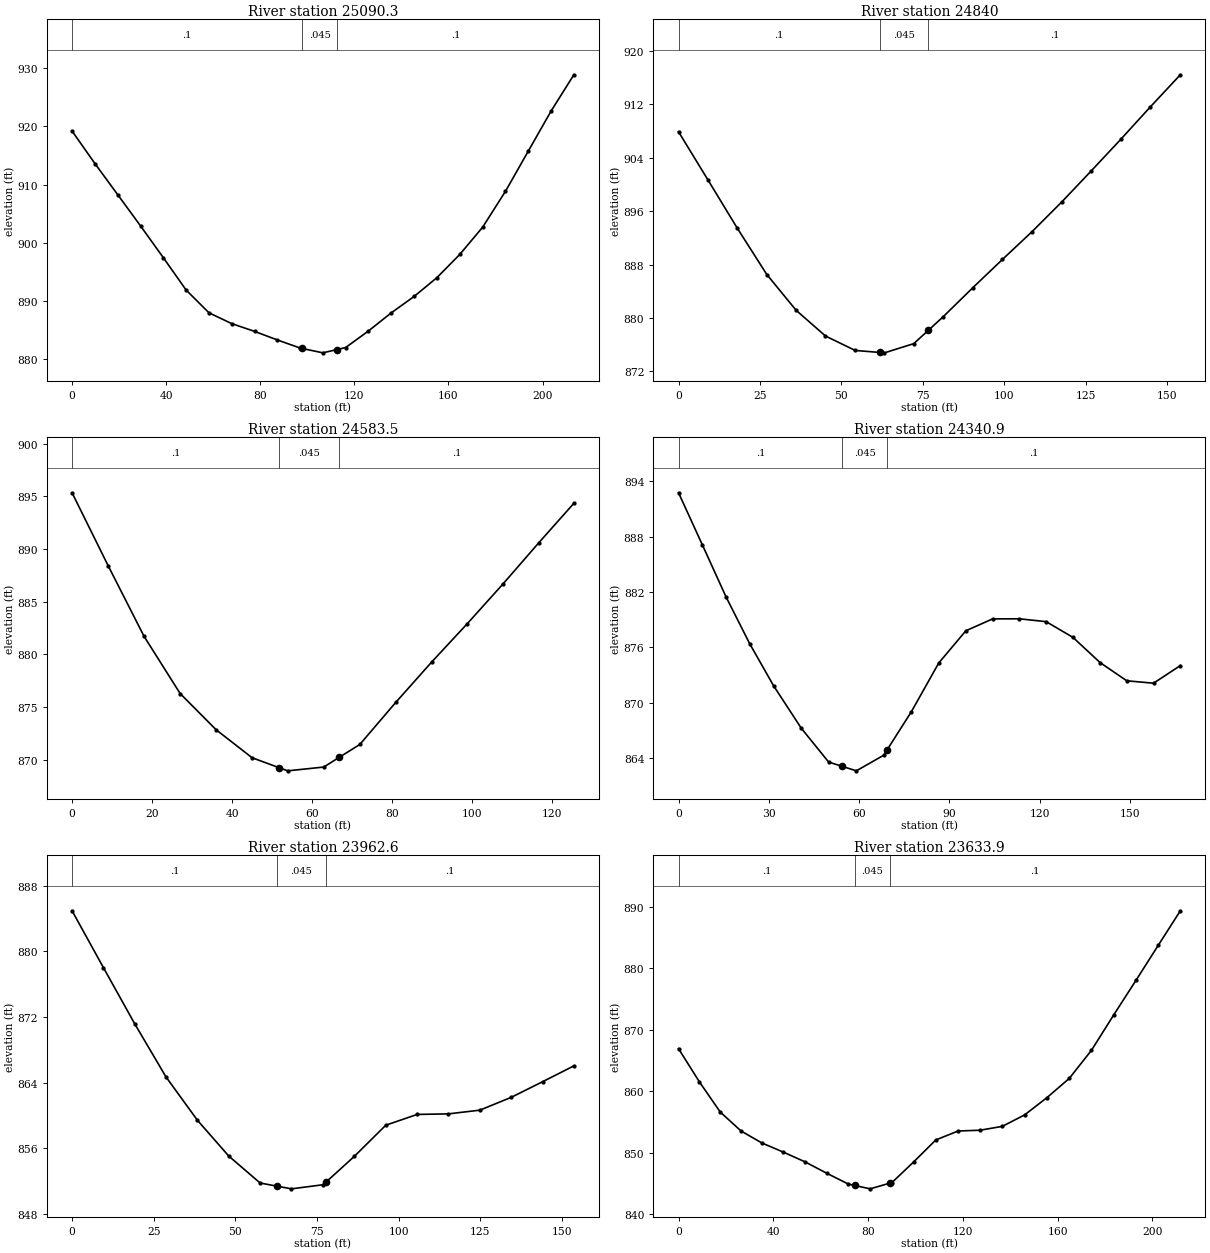
Type RM Length L Ch R = 1 ,25090.3 ,226.7,250.3,272.9
XS GIS Cut Line= 2
     1822310.317      416594.267     1822492.609       416483.59
#Sta/Elev= 25
       0  919.18     9.7  913.61    19.4  908.26    29.1   902.9    38.8  897.44
    48.5  891.88    58.2  887.98    67.9  886.12    77.6  884.79    87.2  883.33
    96.9  881.94    97.7  881.87   106.6  881.11   112.7  881.68   116.3  882.02
     126  884.87   135.7  887.98   145.4  890.79   155.1  894.02   164.8     898
   174.5  902.66   184.2  908.82   193.9  915.72   203.6   922.6   213.3  928.84
#Mann= 3 , 0 , 0
       0      .1       0    97.7    .045       0   112.7      .1       0
Bank Sta=97.7,112.7
XS Rating Curve= 0 ,0
Exp/Cntr=0.3,0.1

Type RM Length L Ch R = 1 ,24840   ,258.1,256.6,255.7
XS GIS Cut Line= 3
     1822337.444      416748.347     1822417.739      416789.579
     1822480.673      416799.345
#Sta/Elev= 20
       0   907.9       9  900.71      18  893.48    27.1  886.51    36.1  881.15
    45.1   877.3    54.2  875.14    61.7  874.84    63.2  874.78    72.2  876.16
    76.7  878.17    81.2  880.18    90.3  884.53    99.4  888.77   108.5  892.94
   117.6  897.38   126.7  902.06   135.8  906.81   144.8  911.63     154  916.44
#Mann= 3 , 0 , 0
       0      .1       0    61.7    .045       0    76.7      .1       0
Bank Sta=61.7,76.7
XS Rating Curve= 0 ,0
Exp/Cntr=0.3,0.1

Type RM Length L Ch R = 1 ,24583.5 ,244.5,242.6,240.6
XS GIS Cut Line= 3
     1822267.999      417001.168     1822350.465      417036.975
     1822385.187      417044.571
#Sta/Elev= 17
       0  895.33       9  888.42      18   881.7      27  876.28      36  872.84
      45  870.18    51.8  869.23    53.9  868.94    62.9   869.3    66.8  870.23
    71.9  871.44    80.9  875.44    89.9  879.28    98.8  882.92   107.7  886.68
   116.6  890.57   125.4  894.33
#Mann= 3 , 0 , 0
       0      .1       0    51.8    .045       0    66.8      .1       0
Bank Sta=51.8,66.8
XS Rating Curve= 0 ,0
Exp/Cntr=0.3,0.1

Type RM Length L Ch R = 1 ,24340.9 ,373.5,378.3,383
XS GIS Cut Line= 4
     1822217.001      417239.883     1822246.298      417251.819
     1822298.381       417269.18     1822374.336      417295.222
#Sta/Elev= 22
       0  892.75     7.9  887.12    15.8  881.46    23.7  876.36    31.6  871.83
    40.8  867.23    49.9  863.56    54.4   863.1    59.1  862.61    68.2   864.3
    69.4  864.92    77.4  869.02    86.5   874.3    95.5  877.79   104.4  879.08
   113.3  879.09   122.2  878.78   131.1  877.08   140.1  874.35     149  872.37
   157.9  872.11   166.8  874.02
#Mann= 3 , 0 , 0
       0      .1       0    54.4    .045       0    69.4      .1       0
Bank Sta=54.4,69.4
XS Rating Curve= 0 ,0
Exp/Cntr=0.3,0.1

Type RM Length L Ch R = 1 ,23962.6 ,335.6,328.7,321.5
XS GIS Cut Line= 2
     1822077.027       417577.34     1822209.406      417655.465
#Sta/Elev= 19
       0  884.94     9.6  878.02    19.2  871.17    28.8  864.69    38.4  859.43
      48  855.07    57.6  851.79    62.7  851.41    67.2  851.08    76.9  851.58
    77.7  851.87    86.5  855.05    96.1  858.83   105.7  860.14   115.3  860.21
   124.9  860.66   134.5  862.22   144.1  864.12   153.7  866.05
#Mann= 3 , 0 , 0
       0      .1       0    62.7    .045       0    77.7      .1       0
Bank Sta=62.7,77.7
XS Rating Curve= 0 ,0
Exp/Cntr=0.3,0.1

Type RM Length L Ch R = 1 ,23633.9 ,359.6,358.1,356.3
XS GIS Cut Line= 4
     1821963.095      417888.755     1821997.817      417915.881
     1822060.751      417929.987     1822163.833      417936.498
#Sta/Elev= 26
       0  866.91     8.8  861.51    17.6   856.6    26.4  853.51    35.2  851.56
    44.1   850.1    53.3  848.51    62.5  846.65    71.7  844.87    74.3  844.65
    80.9   844.1    89.3  845.04    90.1  845.13    99.3   848.5   108.6  852.06
     118  853.51   127.3  853.64   136.7  854.27   146.1  856.14   155.5  858.94
   164.9  862.06   174.3  866.65   183.7  872.41   193.1  878.04   202.5  883.74
   211.8  889.35
#Mann= 3 , 0 , 0
       0      .1       0    74.3    .045       0    89.3      .1       0
Bank Sta=74.3,89.3
XS Rating Curve= 0 ,0
Exp/Cntr=0.3,0.1

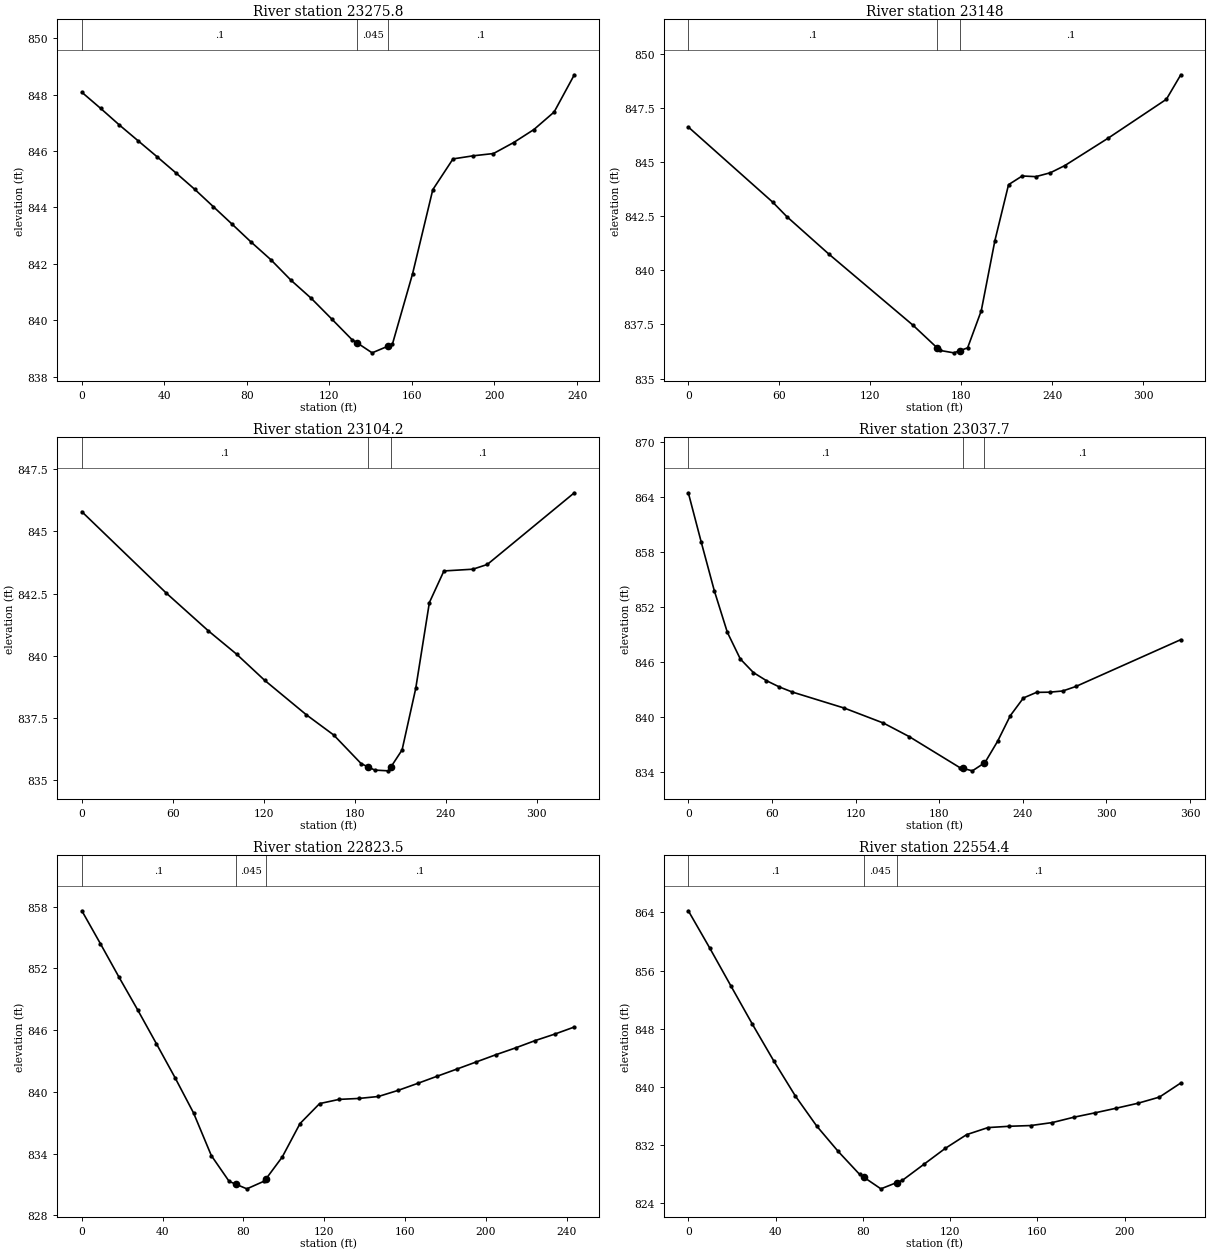
Type RM Length L Ch R = 1 ,23275.8 ,124.9,127.8,130.6
XS GIS Cut Line= 3
     1821867.609       418204.51     1821918.607      418268.529
     1822073.772      418291.315
#Sta/Elev= 28
       0  848.08     9.1  847.51    18.2  846.92    27.3  846.36    36.4   845.8
    45.5  845.23    54.6  844.65    63.7  844.03    72.8  843.41    81.8  842.79
    91.6  842.15   101.4  841.42   111.2  840.78   121.1  840.05   130.9  839.32
   133.5   839.2   140.7  838.85   148.5  839.09   150.5  839.15   160.3  841.65
   170.1  844.63   179.9  845.72   189.7  845.83   199.5  845.91   209.3   846.3
   219.1  846.76   228.9  847.38   238.7   848.7
#Mann= 3 , 0 , 0
       0      .1       0   133.5    .045       0   148.5      .1       0
Bank Sta=133.5,148.5
XS Rating Curve= 0 ,0
Exp/Cntr=0.3,0.1

Type RM Length L Ch R = 1 ,23148   ,43.8,43.8,43.8
XS GIS Cut Line= 5
     1821846.992      418282.635     1821905.586      418366.185
     1821939.223      418397.652     1822017.348      418419.354
     1822112.834      418424.779
#Sta/Elev= 20
       0  846.61    55.7  843.14    64.9  842.48    92.8  840.74   148.1  837.47
   164.1  836.42   166.1   836.3   175.1  836.19   179.1  836.29   184.2  836.42
   193.2  838.13   202.2  841.37   211.2  843.95   220.2  844.35   229.2  844.32
   238.8   844.5   248.3  844.83     277   846.1   315.3  847.89   324.8  849.02
#Mann= 3 , 0 , 0
       0      .1       0   164.1    .045       0   179.1      .1       0
Bank Sta=164.1,179.1
XS Rating Curve= 0 ,0
Exp/Cntr=0.3,0.1

Type RM Length L Ch R = 1 ,23104.2 ,70.9,66.6,62.2
XS GIS Cut Line= 5
     1821818.781      418319.527     1821877.374      418403.077
     1821911.011      418434.545     1821989.136      418456.246
     1822084.623      418461.671
#Sta/Elev= 19
       0  845.79    55.7  842.52    83.5     841     102  840.07   120.5  839.02
   148.1  837.63   166.1  836.82   184.2  835.67     189  835.53   193.2  835.41
   202.2  835.38     204  835.55   211.2  836.22   220.2  838.69   229.2  842.14
   238.8  843.41   257.9  843.48   267.4  843.67   324.8  846.55
#Mann= 3 , 0 , 0
       0      .1       0     189    .045       0     204      .1       0
Bank Sta=189,204
XS Rating Curve= 0 ,0
Exp/Cntr=0.3,0.1

Type RM Length L Ch R = 1 ,23037.7 ,210.2,214.2,217.9
XS GIS Cut Line= 4
     1821748.251       418523.52     1821896.906      418509.414
     1821978.286      418515.925     1822099.814      418530.031
#Sta/Elev= 25
       0  864.49     9.3  859.09    18.7  853.78      28  849.27    37.3  846.36
    46.7  844.88      56     844    65.3  843.31    74.7  842.75     112     841
     140  839.37   158.4   837.9   194.7  834.52   197.2  834.42   203.8  834.16
   212.2     835   212.8  835.06   221.9  837.39     231  840.18   240.4  842.11
   249.8  842.72   259.2  842.74   268.6  842.87     278  843.36   353.3  848.47
#Mann= 3 , 0 , 0
       0      .1       0   197.2    .045       0   212.2      .1       0
Bank Sta=197.2,212.2
XS Rating Curve= 0 ,0
Exp/Cntr=0.3,0.1

Type RM Length L Ch R = 1 ,22823.5 ,264.9,269.1,273.1
XS GIS Cut Line= 4
     1821843.737      418718.833     1821899.076      418718.833
     1821950.074      418731.854     1822084.623        418750.3
#Sta/Elev= 29
       0  857.59     9.2  854.39    18.4  851.14    27.7  847.94    36.9  844.68
    46.1  841.39    55.3  837.95    64.1  833.81    72.9  831.31    76.1  831.04
    81.7  830.58    90.4  831.34    91.1  831.53    99.2  833.67     108  836.92
   117.7  838.86   127.4  839.27   137.1  839.36   146.8  839.55   156.5  840.14
   166.2  840.82   175.9  841.52   185.6  842.21   195.3  842.91     205  843.61
   214.7  844.27   224.4  844.98   234.1  845.61   243.8   846.3
#Mann= 3 , 0 , 0
       0      .1       0    76.1    .045       0    91.1      .1       0
Bank Sta=76.1,91.1
XS Rating Curve= 0 ,0
Exp/Cntr=0.3,0.1

Type RM Length L Ch R = 1 ,22554.4 ,150.5,151.6,152.3
XS GIS Cut Line= 2
     1821760.187      418943.442     1821965.265      419037.843
#Sta/Elev= 26
       0  864.23     9.8  859.12    19.6  853.86    29.4  848.63    39.3  843.53
    49.1  838.76    58.9  834.63    68.7  831.16    78.5  828.01    80.6  827.58
    88.3  826.01    95.6  826.88    98.2  827.19     108  829.38   117.8  831.57
   127.6  833.46   137.4  834.43   147.2  834.61     157  834.71   166.9  835.12
   176.7  835.85   186.5  836.46   196.3   837.1   206.1  837.77     216  838.62
   225.8  840.56
#Mann= 3 , 0 , 0
       0      .1       0    80.6    .045       0    95.6      .1       0
Bank Sta=80.6,95.6
XS Rating Curve= 0 ,0
Exp/Cntr=0.3,0.1

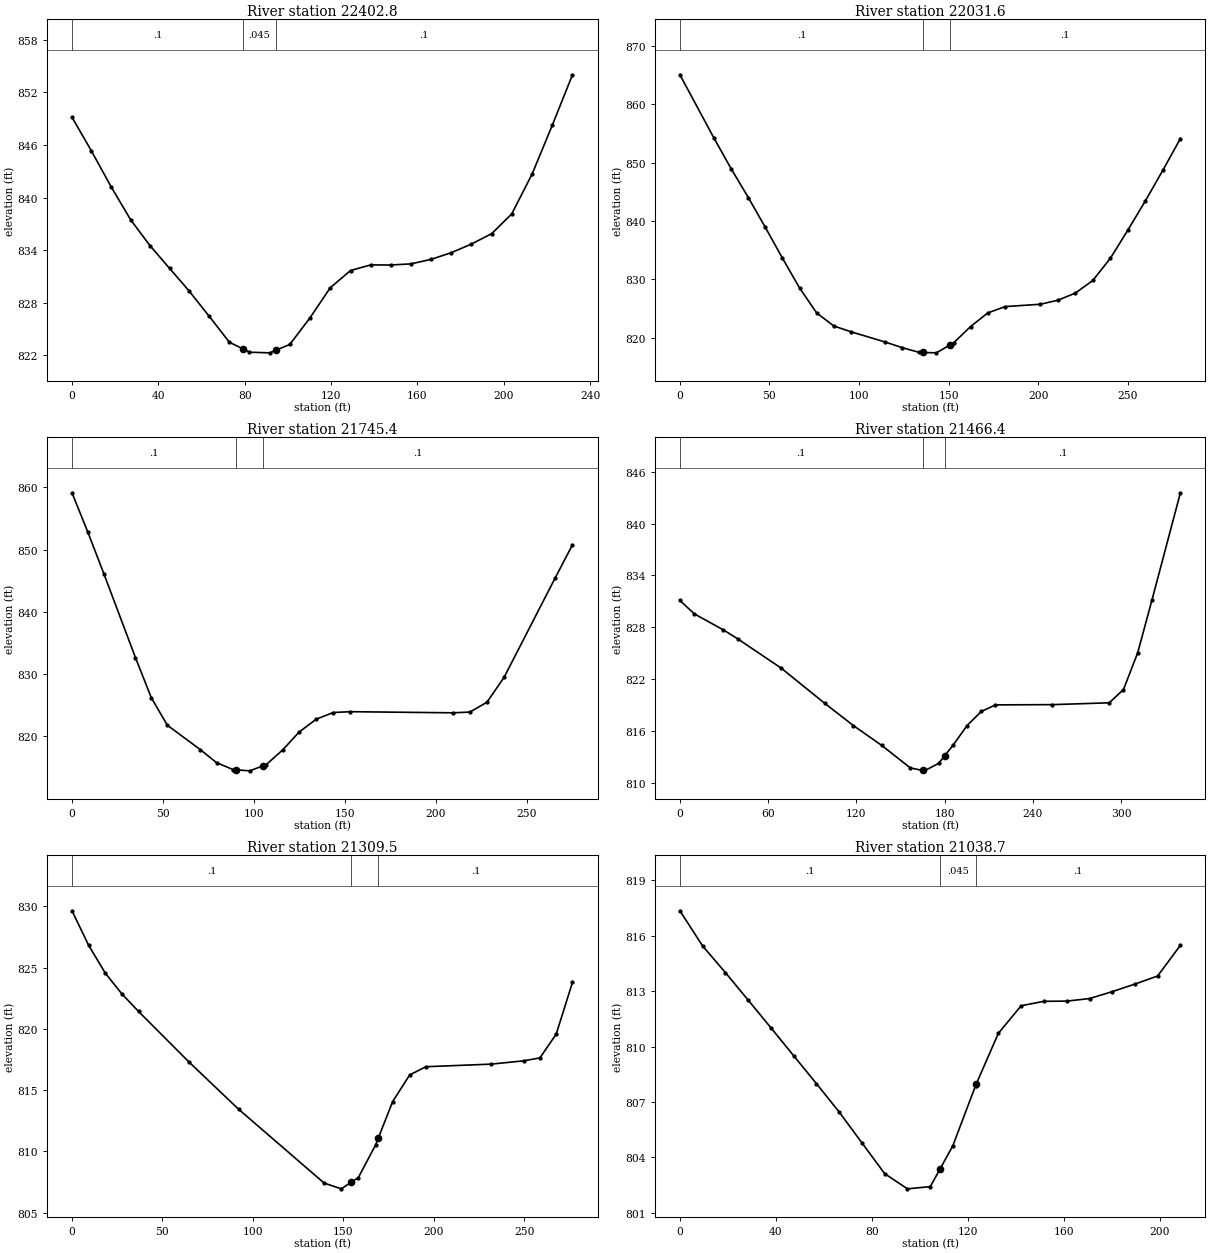
Type RM Length L Ch R = 1 ,22402.8 ,380.7,371.3,361.1
XS GIS Cut Line= 3
     1821736.315      419063.885     1821765.612      419109.458
     1821924.032      419189.753
#Sta/Elev= 28
       0  849.16       9  845.32    18.1  841.24    27.1  837.49    36.1  834.53
    45.2  831.92    54.2  829.36    63.5  826.47    72.9   823.5    79.3  822.72
    82.2  822.36    91.6  822.29    94.3  822.57   100.9  823.25   110.3  826.31
   119.6  829.71     129  831.68   138.3  832.32   147.6  832.31     157  832.44
   166.4  832.96   175.7  833.72     185   834.7   194.4  835.89   203.7  838.15
   213.1  842.69   222.4  848.23   231.8  854.01
#Mann= 3 , 0 , 0
       0      .1       0    79.3    .045       0    94.3      .1       0
Bank Sta=79.3,94.3
XS Rating Curve= 0 ,0
Exp/Cntr=0.3,0.1

Type RM Length L Ch R = 1 ,22031.6 ,290.3,286.2,281.9
XS GIS Cut Line= 4
     1821556.194      419487.062     1821632.149      419479.466
     1821727.635      419482.722     1821835.057      419479.466
#Sta/Elev= 29
       0  865.05    19.1  854.16    28.6  848.96    38.2  844.02    47.7  838.91
    57.2  833.67    66.8  828.54    76.3  824.28    85.9  822.03    95.4  821.05
   114.6  819.28   124.1  818.32   133.7   817.5   135.6  817.49   143.2  817.43
   150.6  818.75   152.8  819.14   162.3  821.94   171.9  824.27   181.6  825.35
   201.2  825.75     211  826.44   220.7  827.65   230.5  829.82   240.3  833.62
     250  838.41   259.8  843.43   269.6  848.69   279.4  854.12
#Mann= 3 , 0 , 0
       0      .1       0   135.6    .045       0   150.6      .1       0
Bank Sta=135.6,150.6
XS Rating Curve= 0 ,0
Exp/Cntr=0.3,0.1

Type RM Length L Ch R = 1 ,21745.4 ,283.4,279,273.5
XS GIS Cut Line= 4
      1821572.47      419784.371     1821623.468      419772.435
     1821695.083      419761.584     1821840.482      419723.607
#Sta/Elev= 24
       0  859.14     8.7  852.82    17.5  846.15    34.9  832.65    43.6  826.22
    52.4  821.81    70.5  817.89    79.5  815.78    88.6  814.68    90.2  814.64
    97.6  814.48   105.2   815.3   106.7  815.46   115.8  817.84   124.8   820.7
   134.2  822.77   143.6  823.85     153  823.98   209.3   823.8   218.7  823.92
   228.1   825.5   237.5   829.5   265.7  845.53   275.1  850.78
#Mann= 3 , 0 , 0
       0      .1       0    90.2    .045       0   105.2      .1       0
Bank Sta=90.2,105.2
XS Rating Curve= 0 ,0
Exp/Cntr=0.3,0.1

Type RM Length L Ch R = 1 ,21466.4 ,159.4,156.9,154.4
XS GIS Cut Line= 3
     1821596.341      420030.682     1821713.529      420043.702
     1821920.777      419963.407
#Sta/Elev= 23
       0   831.1     9.8  829.55    29.5   827.7    39.3  826.66    68.8  823.28
    98.3  819.22   117.9  816.63   137.2  814.33   156.6  811.73     165  811.43
   166.2  811.39   175.9  812.26     180  813.14   185.6  814.34   195.2  816.63
   204.9  818.26   214.5  819.02   253.2  819.05   291.8  819.26   301.5  820.79
   311.2  825.06   320.8   831.1   340.2  843.56
#Mann= 3 , 0 , 0
       0      .1       0     165    .045       0     180      .1       0
Bank Sta=165,180
XS Rating Curve= 0 ,0
Exp/Cntr=0.3,0.1

Type RM Length L Ch R = 1 ,21309.5 ,277.9,270.7,263.6
XS GIS Cut Line= 4
     1821698.338      420220.569     1821784.058      420186.932
     1821867.609      420142.444     1821952.244      420112.062
#Sta/Elev= 21
       0  829.64     9.2  826.82    18.4  824.55    27.6  822.85    36.8  821.42
    64.5  817.32    92.1  813.44   139.4  807.41   148.9  806.94   154.3  807.47
   158.3  807.86   167.8  810.51   169.3  811.07   177.3  814.07   186.7  816.24
   195.7  816.91   231.7  817.12   249.7  817.39   258.7  817.63   267.7  819.57
   276.7   823.8
#Mann= 3 , 0 , 0
       0      .1       0   154.3    .045       0   169.3      .1       0
Bank Sta=154.3,169.3
XS Rating Curve= 0 ,0
Exp/Cntr=0.3,0.1

Type RM Length L Ch R = 1 ,21038.7 ,340,338.7,337.3
XS GIS Cut Line= 2
     1821934.883      420446.263     1822081.367      420297.609
#Sta/Elev= 25
       0  817.35     9.5  815.44      19     814    28.5  812.51      38  811.01
    47.4  809.51    56.9     808    66.4  806.46    75.9  804.79    85.4  803.12
    94.9   802.3   104.4  802.42   108.5  803.38   113.8  804.63   123.3  807.89
   123.5  807.95   132.8  810.72   142.3  812.21   151.8  812.45   161.3  812.46
   170.8   812.6   180.2  812.97   189.7  813.38   199.2  813.82   208.7  815.48
#Mann= 3 , 0 , 0
       0      .1       0   108.5    .045       0   123.5      .1       0
Bank Sta=108.5,123.5
XS Rating Curve= 0 ,0
Exp/Cntr=0.3,0.1

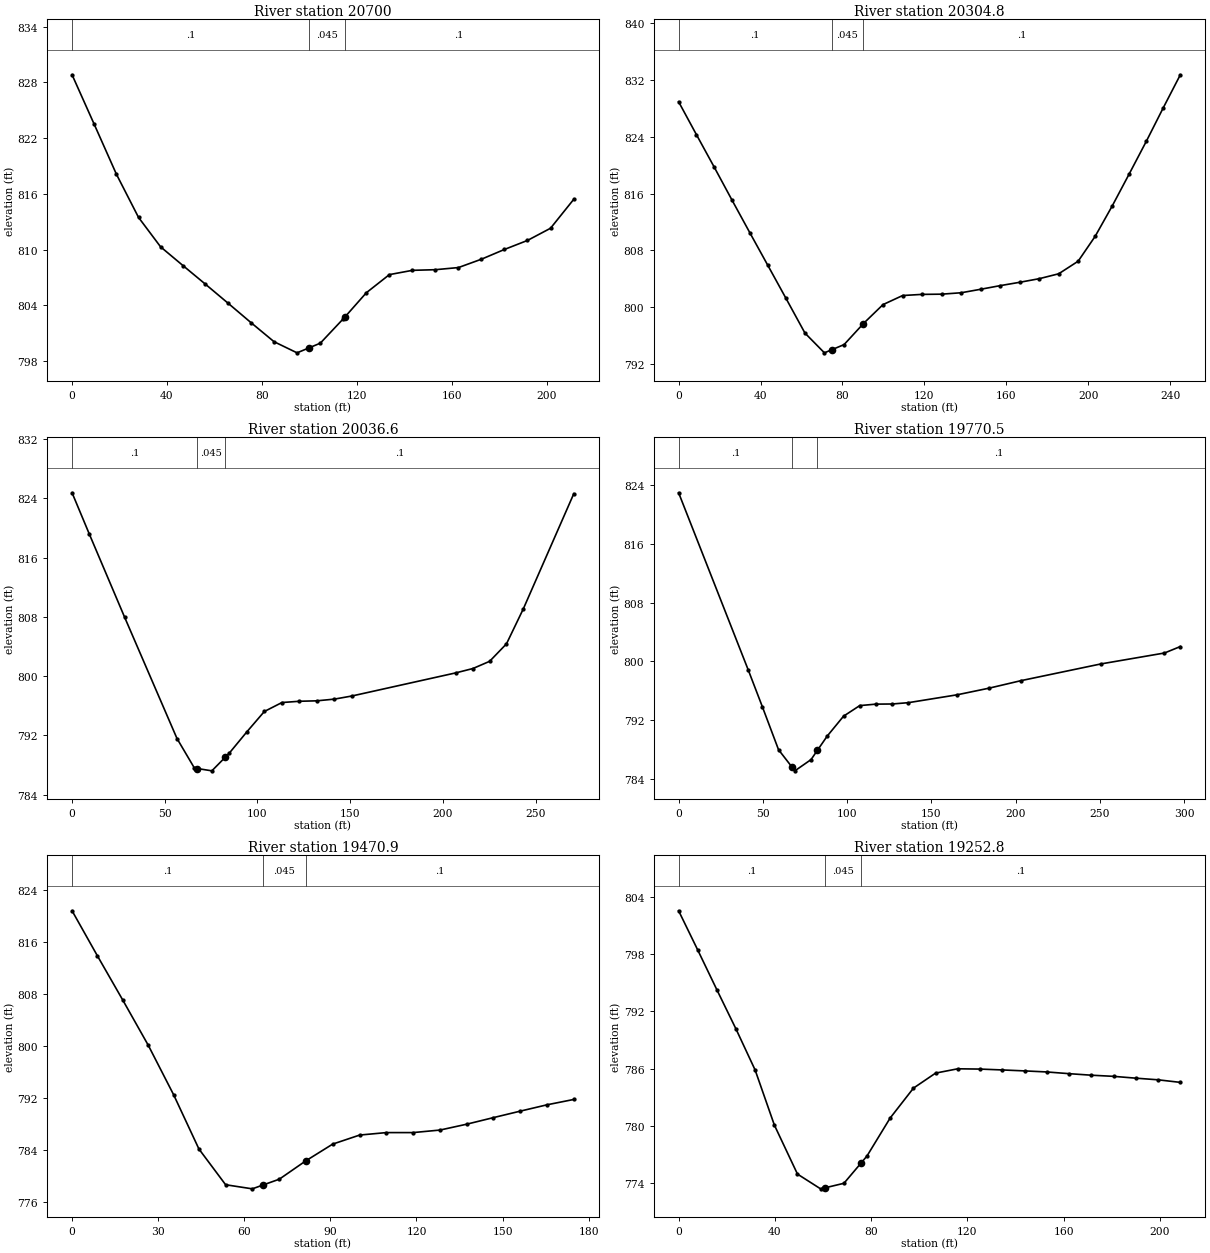
Type RM Length L Ch R = 1 ,20700   ,392.4,395.3,397.9
XS GIS Cut Line= 3
      1822208.32      420666.532     1822240.873      420620.959
     1822342.869      420503.772
#Sta/Elev= 25
       0  828.82     9.3  823.51    18.7  818.11      28  813.47    37.3   810.3
    46.7  808.29      56  806.32    65.7  804.24    75.4  802.14    85.1  800.09
    94.8  798.89    99.8  799.42   104.6  799.93   114.3  802.56   114.8   802.7
     124  805.36   133.7  807.31   143.4  807.77   153.1  807.84   162.8  808.07
   172.5  808.97   182.2  810.02   191.9  810.99   201.6   812.3   211.4  815.42
#Mann= 3 , 0 , 0
       0      .1       0    99.8    .045       0   114.8      .1       0
Bank Sta=99.8,114.8
XS Rating Curve= 0 ,0
Exp/Cntr=0.3,0.1

Type RM Length L Ch R = 1 ,20304.8 ,265.3,268.2,271.1
XS GIS Cut Line= 4
     1822526.246      420883.546     1822562.053      420845.569
      1822668.39      420750.083     1822704.197       420715.36
#Sta/Elev= 30
       0  828.94     8.7  824.31    17.4  819.73    26.1  815.08    34.8  810.49
    43.5  805.94    52.2  801.38    61.7  796.37    71.2  793.59    74.9  794.04
    80.8  794.75    89.9   797.6    90.3  797.73    99.8  800.38   109.4  801.66
   118.9  801.82   128.4  801.85     138  802.05   147.5  802.54     157  803.05
   166.5  803.52   176.1  804.03   185.6  804.72   195.1  806.49   203.4  809.99
   211.7  814.25     220  818.76   228.4  823.38   236.7  828.11     245  832.74
#Mann= 3 , 0 , 0
       0      .1       0    74.9    .045       0    89.9      .1       0
Bank Sta=74.9,89.9
XS Rating Curve= 0 ,0
Exp/Cntr=0.3,0.1

Type RM Length L Ch R = 1 ,20036.6 ,264.8,266,267
XS GIS Cut Line= 3
     1822690.091      421075.604     1822852.852      420962.756
     1822898.425      420906.333
#Sta/Elev= 22
       0  824.74     9.4  819.11    28.3  807.97    56.6  791.57      66  787.58
    67.6  787.52    75.4  787.21    82.6  789.04    84.9  789.63    94.3  792.48
   103.7  795.22   113.2  796.43   122.6   796.6     132  796.66   141.5  796.89
   150.9  797.31   207.1  800.44   216.2  801.02   225.2  801.99   234.3  804.35
   243.4  809.08   270.6  824.61
#Mann= 3 , 0 , 0
       0      .1       0    67.6    .045       0    82.6      .1       0
Bank Sta=67.6,82.6
XS Rating Curve= 0 ,0
Exp/Cntr=0.3,0.1

Type RM Length L Ch R = 1 ,19770.5 ,296.5,299.6,302.6
XS GIS Cut Line= 4
     1822843.086      421287.192     1822885.404       421261.15
     1822991.741      421194.961     1823051.419      421087.539
#Sta/Elev= 20
       0  822.96    41.4   798.8    49.7  793.84    59.3  787.99    67.4  785.59
      69  785.11    78.6  786.64    82.4  787.91    88.2  789.84    97.9  792.55
   107.5  793.99   117.1  794.19   126.8  794.21   136.4  794.39   165.3  795.46
   184.4  796.37   203.3  797.39   250.6  799.66   288.4  801.15   297.8  802.03
#Mann= 3 , 0 , 0
       0      .1       0    67.4    .045       0    82.4      .1       0
Bank Sta=67.4,82.4
XS Rating Curve= 0 ,0
Exp/Cntr=0.3,0.1

Type RM Length L Ch R = 1 ,19470.9 ,206.5,218.1,229.8
XS GIS Cut Line= 3
     1822991.741      421535.673     1823031.888      421517.227
     1823151.246      421464.058
#Sta/Elev= 21
       0  820.76     8.8  813.86    17.7  807.02    26.5  800.14    35.4  792.49
    44.2  784.17    53.5  778.68    62.8  778.05    66.4  778.62    72.2  779.53
    81.4  782.34    90.8  784.92   100.2  786.31   109.5  786.69   118.8  786.69
   128.2  787.08   137.5  787.98   146.8  788.99   156.2  789.99   165.5  790.96
   174.8  791.78
#Mann= 3 , 0 , 0
       0      .1       0    66.4    .045       0    81.4      .1       0
Bank Sta=66.4,81.4
XS Rating Curve= 0 ,0
Exp/Cntr=0.3,0.1

Type RM Length L Ch R = 1 ,19252.8 ,285,283.3,281.6
XS GIS Cut Line= 4
     1823002.591      421700.604     1823038.399      421717.965
     1823095.907       421723.39     1823206.584      421730.985
#Sta/Elev= 26
       0  802.51       8  798.38    15.9  794.25    23.9  790.12    31.8  785.86
    39.8   780.1    49.4  774.98      59  773.44    60.9  773.55    68.7  774.02
    75.9  776.16    78.3  776.88    87.9  780.84    97.6  783.97   106.8  785.54
     116  785.99   125.3  785.96   134.5  785.87   143.8  785.77     153  785.66
   162.3  785.48   171.5  785.32   180.8   785.2     190  785.01   199.2  784.84
   208.5  784.57
#Mann= 3 , 0 , 0
       0      .1       0    60.9    .045       0    75.9      .1       0
Bank Sta=60.9,75.9
XS Rating Curve= 0 ,0
Exp/Cntr=0.3,0.1

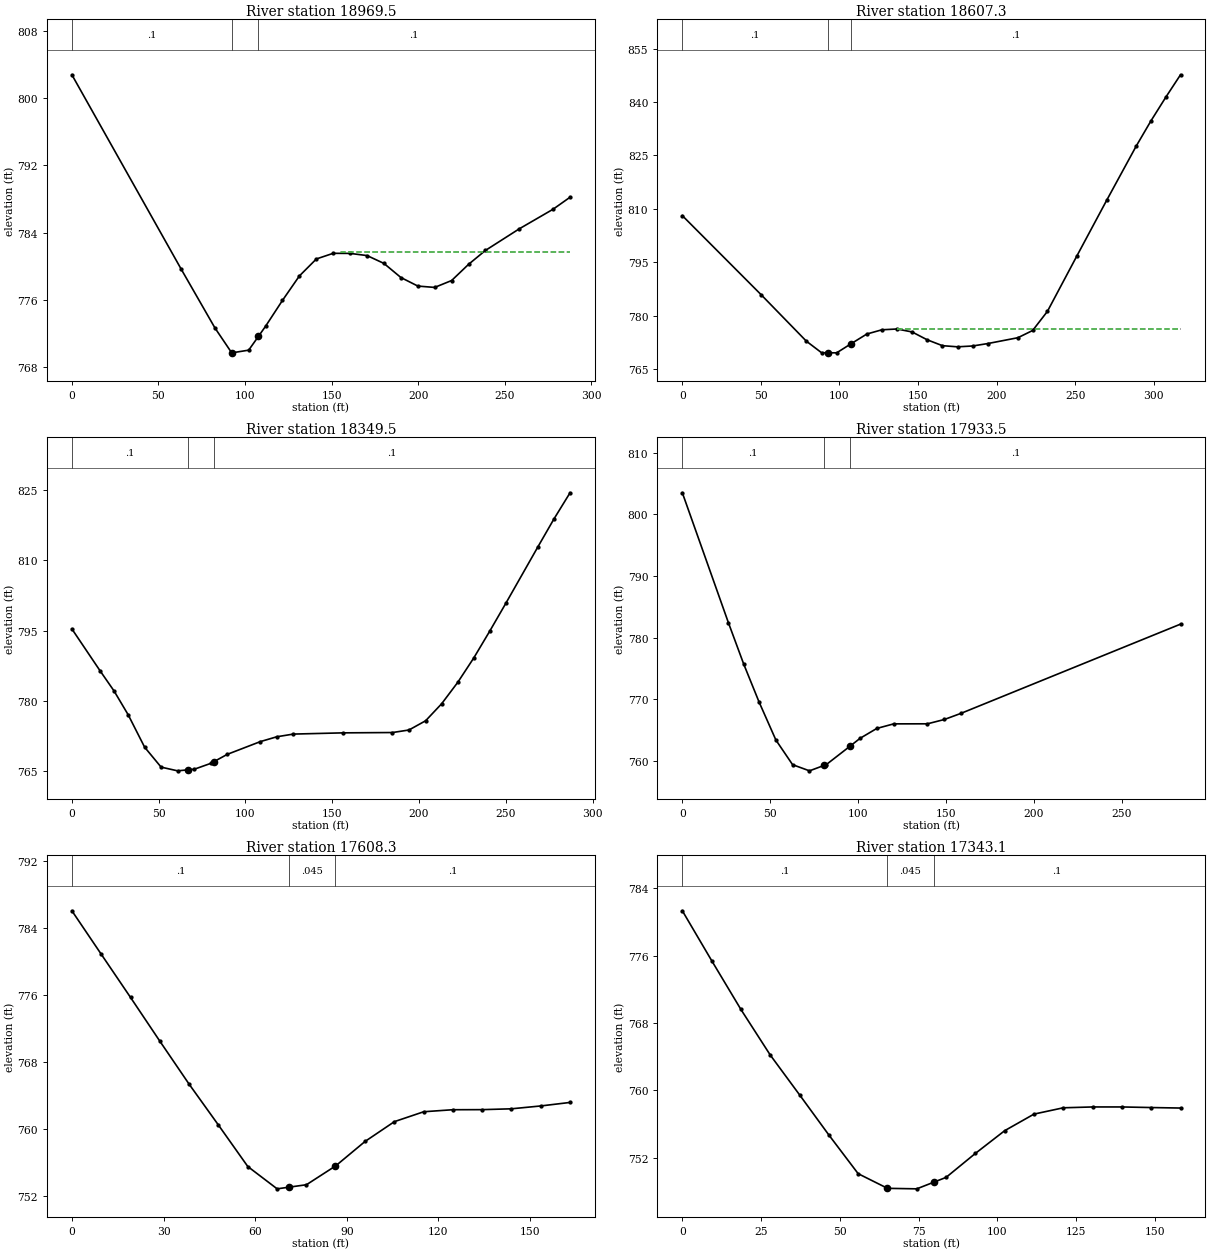
Type RM Length L Ch R = 1 ,18969.5 ,359.2,362.1,364.9
XS GIS Cut Line= 3
     1822920.126      421995.742      1822983.06      421998.998
     1823207.669      422003.338
#Sta/Elev= 24
       0   802.8      63   779.7    82.6  772.66    92.3  769.69    92.7   769.7
   102.1  770.01   107.7  771.64   111.9  772.87   121.6  775.93   131.4  778.85
   141.2  780.87   150.9  781.54   160.7  781.53   170.5  781.27   180.2  780.34
     190  778.66   199.8  777.64   209.5  777.48   219.3   778.3   229.1  780.23
   238.8  781.88   258.4  784.46   277.9  786.79   287.7  788.22
#Mann= 3 , 0 , 0
       0      .1       0    92.7    .045       0   107.7      .1       0
#XS Ineff= 2 , 0
                          155.45          781.73
Permanent Ineff=
       F       F
Bank Sta=92.7,107.7
XS Rating Curve= 0 ,0
Exp/Cntr=0.3,0.1

Type RM Length L Ch R = 1 ,18607.3 ,254.7,257.8,260.5
XS GIS Cut Line= 4
     1822891.914      422357.071     1822941.827       422352.73
     1823103.503      422376.602     1823205.499      422393.963
#Sta/Elev= 25
       0  808.11    50.1  785.94    78.9  772.89    88.6  769.64    92.4  769.63
    98.2  769.61   107.4  772.17   117.4  774.89     127  776.08   136.6   776.3
   146.2  775.47   155.8  773.27   165.5  771.62   175.1   771.3   184.7  771.53
   194.3  772.21   213.5  773.85   222.9  775.88   232.3  781.24   251.2  796.92
     270   812.4   288.8  827.62   298.2  834.71   307.6  841.32     317  847.64
#Mann= 3 , 0 , 0
       0      .1       0    92.4    .045       0   107.4      .1       0
#XS Ineff= 2 , 0
                           136.4          776.33
Permanent Ineff=
       F       F
Bank Sta=92.4,107.4
XS Rating Curve= 0 ,0
Exp/Cntr=0.3,0.1

Type RM Length L Ch R = 1 ,18349.5 ,415.2,416,416.7
XS GIS Cut Line= 4
     1822884.319       422581.68     1822909.275      422602.296
     1823074.206      422648.954     1823154.501      422627.253
#Sta/Elev= 27
       0  795.35    16.2  786.45    24.3  782.13    32.4  777.08    41.9  770.16
    51.4  765.91    60.9  765.12    66.8  765.33    70.5  765.46      80  766.71
    81.8  767.07    89.5  768.63   108.6  771.35   118.1  772.38   127.6  772.95
   156.2  773.21   184.7  773.28   194.2  773.82   203.8  775.79     213   779.4
   222.3  783.97   231.5  789.15   240.7  794.86     250  800.81   268.5  812.85
   277.7  818.76     287  824.35
#Mann= 3 , 0 , 0
       0      .1       0    66.8    .045       0    81.8      .1       0
Bank Sta=66.8,81.8
XS Rating Curve= 0 ,0
Exp/Cntr=0.3,0.1

Type RM Length L Ch R = 1 ,17933.5 ,318.4,325.1,331.8
XS GIS Cut Line= 4
     1822819.215      422995.091     1822860.447      423009.197
     1822970.039       423043.92     1823094.822      423045.005
#Sta/Elev= 17
       0  803.48    26.2   782.4    34.9  775.69    43.6  769.56    53.2  763.37
    62.7  759.37    72.3  758.37    80.5  759.24    81.9  759.39    95.5   762.4
   101.1  763.65   110.6  765.25   120.2  765.99   139.4     766     149   766.7
   158.5   767.7   283.3  782.17
#Mann= 3 , 0 , 0
       0      .1       0    80.5    .045       0    95.5      .1       0
Bank Sta=80.5,95.5
XS Rating Curve= 0 ,0
Exp/Cntr=0.3,0.1

Type RM Length L Ch R = 1 ,17608.3 ,261.4,265.2,268.6
XS GIS Cut Line= 2
      1822745.43       423288.06     1822879.978      423380.291
#Sta/Elev= 20
       0  786.02     9.6  780.84    19.2  775.68    28.8  770.46    38.4  765.32
      48  760.44    57.6   755.5    67.2  752.84    71.1  753.04    76.8  753.33
    86.1  755.52    86.4  755.59      96   758.5   105.6  760.86   115.2  762.04
   124.7  762.28   134.3  762.29   143.9  762.39   153.5  762.73   163.1  763.15
#Mann= 3 , 0 , 0
       0      .1       0    71.1    .045       0    86.1      .1       0
Bank Sta=71.1,86.1
XS Rating Curve= 0 ,0
Exp/Cntr=0.3,0.1

Type RM Length L Ch R = 1 ,17343.1 ,223,221.7,219.9
XS GIS Cut Line= 2
     1822616.307      423501.819     1822730.239      423611.411
#Sta/Elev= 20
       0  781.35     9.3  775.43    18.6  769.62    27.9  764.21    37.2  759.48
    46.5  754.71    55.8  750.11    64.8  748.43    65.1  748.37    74.4  748.31
    79.8   749.1    83.7  749.67      93  752.52   102.3  755.22   111.6  757.19
   120.9  757.94   130.2  758.04   139.5  758.04   148.8  757.97   158.1  757.91
#Mann= 3 , 0 , 0
       0      .1       0    64.8    .045       0    79.8      .1       0
Bank Sta=64.8,79.8
XS Rating Curve= 0 ,0
Exp/Cntr=0.3,0.1

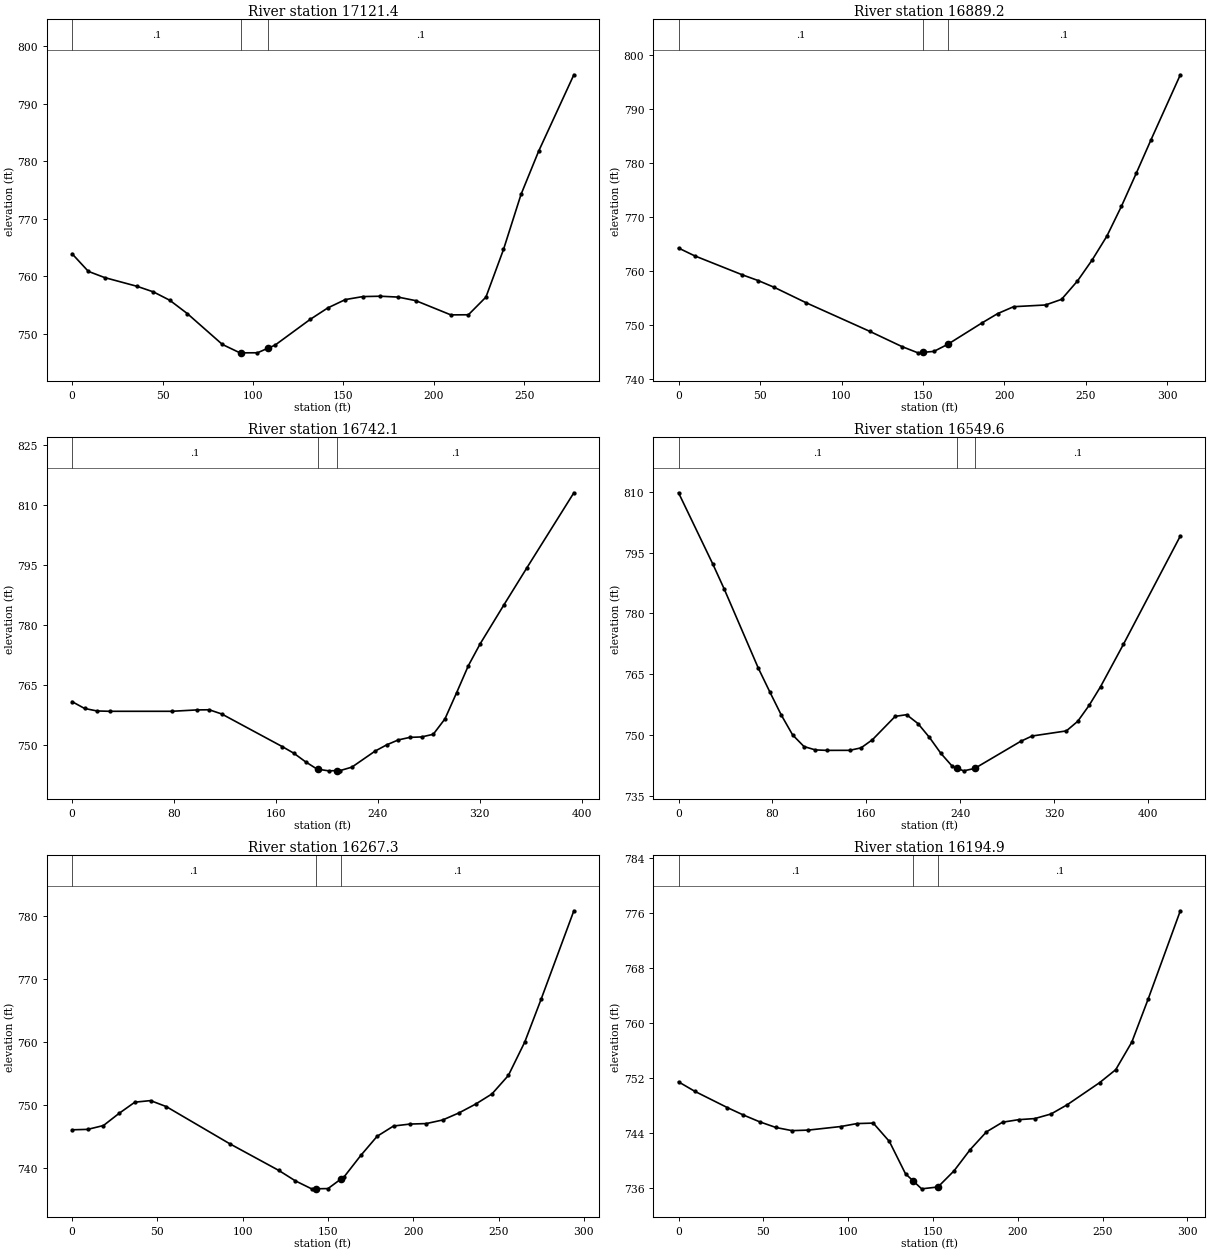
Type RM Length L Ch R = 1 ,17121.4 ,230.6,232.2,233.9
XS GIS Cut Line= 3
     1822463.312      423643.963     1822490.439      423690.621
     1822661.879       423833.85
#Sta/Elev= 27
       0   763.9       9  760.83      18  759.75      36  758.22      45  757.25
      54   755.8    63.7  753.48    83.1   748.1    92.8  746.64    93.3  746.64
   102.5  746.65   108.3  747.45   112.2  747.98   131.7  752.48   141.4  754.47
   151.1  755.92   160.8  756.44   170.5   756.5   180.2  756.35     190  755.73
   209.4  753.25   219.1  753.27   228.8  756.35   238.5  764.64   248.2  774.24
   257.9  781.74   277.4  795.07
#Mann= 3 , 0 , 0
       0      .1       0    93.3    .045       0   108.3      .1       0
Bank Sta=93.3,108.3
XS Rating Curve= 0 ,0
Exp/Cntr=0.3,0.1

Type RM Length L Ch R = 1 ,16889.2 ,150.4,147.1,143.4
XS GIS Cut Line= 3
     1822273.425      423793.702     1822449.206      423964.058
     1822490.439      424011.801
#Sta/Elev= 24
       0  764.28     9.8  762.85    39.2  759.31      49  758.24    58.8  756.99
    78.3  754.14   117.5  748.82   137.1  746.02   146.9  744.86   150.2  744.95
   156.7  745.13   165.2  746.44     186  750.37   195.8  752.13   205.6  753.41
   225.2  753.73     235  754.77   244.8  758.18   253.8  762.07   262.8  766.47
   271.8  772.04   280.8   778.1   289.8  784.27   307.9  796.39
#Mann= 3 , 0 , 0
       0      .1       0   150.2    .045       0   165.2      .1       0
Bank Sta=150.2,165.2
XS Rating Curve= 0 ,0
Exp/Cntr=0.3,0.1

Type RM Length L Ch R = 1 ,16742.1 ,206.1,192.5,178.7
XS GIS Cut Line= 4
     1822123.685      423903.295     1822247.383      423982.505
     1822343.954      424050.864     1822455.716      424114.883
#Sta/Elev= 30
       0  760.91     9.8  759.21    19.6  758.58    29.4   758.5    78.3   758.5
    97.9  758.84   107.7  758.88   117.5  757.83   165.1  749.68   174.2  748.02
   183.3   745.9   192.4  744.07     193  744.04   201.5  743.64     208   743.7
   210.6  743.72   219.7  744.56   237.9  748.56     247  750.12   256.1  751.35
   265.2  751.99   274.4   752.1   283.6  752.76   292.8  756.61     302  763.18
   311.2  769.91   320.4  775.32   338.8  784.91   357.2  794.35     394  813.03
#Mann= 3 , 0 , 0
       0      .1       0     193    .045       0     208      .1       0
Bank Sta=193,208
XS Rating Curve= 0 ,0
Exp/Cntr=0.3,0.1

Type RM Length L Ch R = 1 ,16549.6 ,287.1,282.3,277
XS GIS Cut Line= 2
     1821995.647      424195.178     1822423.164      424198.433
#Sta/Elev= 30
       0  809.75    29.2  792.17    38.9  786.02      68  766.47    77.7  760.67
    87.4     755    97.2  750.02   106.9  747.15   116.6  746.32   126.3  746.21
   145.8  746.22   155.5  746.83   165.2  748.84   184.6   754.6   194.3  755.01
     204  752.82   213.8  749.39   223.5  745.47   233.2  742.29   237.3  741.81
   242.9  741.16   252.3  741.75   291.5  748.44   301.2  749.75   330.4  751.01
   340.1  753.38   349.8  757.31   359.5   761.9     379  772.36   427.5  799.09
#Mann= 3 , 0 , 0
       0      .1       0   237.3    .045       0   252.3      .1       0
Bank Sta=237.3,252.3
XS Rating Curve= 0 ,0
Exp/Cntr=0.3,0.1

Type RM Length L Ch R = 1 ,16267.3 ,72.8,72.3,71.9
XS GIS Cut Line= 3
     1822167.088      424451.255     1822246.298      424475.126
     1822452.461      424428.468
#Sta/Elev= 28
       0   746.1     9.2  746.17    18.4  746.78    27.6  748.72    36.8  750.49
      46  750.74    55.2  749.79    92.3   743.9   121.2  739.64   130.8     738
   140.4  736.72   142.7  736.73     150  736.76   157.7   738.3   159.6  738.68
   169.2  742.02   178.8  745.07   188.4   746.7     198  747.01   207.6  747.09
   217.2  747.66   226.8  748.79   236.5  750.18   246.1   751.8   255.7  754.73
   265.3  760.03   274.9  766.84   294.1   780.9
#Mann= 3 , 0 , 0
       0      .1       0   142.7    .045       0   157.7      .1       0
Bank Sta=142.7,157.7
XS Rating Curve= 0 ,0
Exp/Cntr=0.3,0.1

Type RM Length L Ch R = 1 ,16194.9 ,58.4,66.9,74.8
XS GIS Cut Line= 3
     1822181.194      424565.187     1822292.956      424539.145
     1822468.737      424495.742
#Sta/Elev= 30
       0   751.4     9.6  750.02    28.7  747.66    38.2  746.57    47.8  745.58
    57.4  744.75    66.9  744.29    76.5  744.37    95.6  744.89   105.2  745.32
   114.8  745.39   124.3  742.71   133.8     738   138.2  736.99   143.3  735.81
   152.9  736.08   153.2  736.15   162.4  738.43   171.9  741.52   181.5  744.11
     191  745.52   200.5  745.89     210  746.05   219.6  746.72   229.1  748.06
   248.2  751.28   257.7  753.17   267.2  757.19   276.8  763.44   295.8  776.33
#Mann= 3 , 0 , 0
       0      .1       0   138.2    .045       0   153.2      .1       0
Bank Sta=138.2,153.2
XS Rating Curve= 0 ,0
Exp/Cntr=0.3,0.1