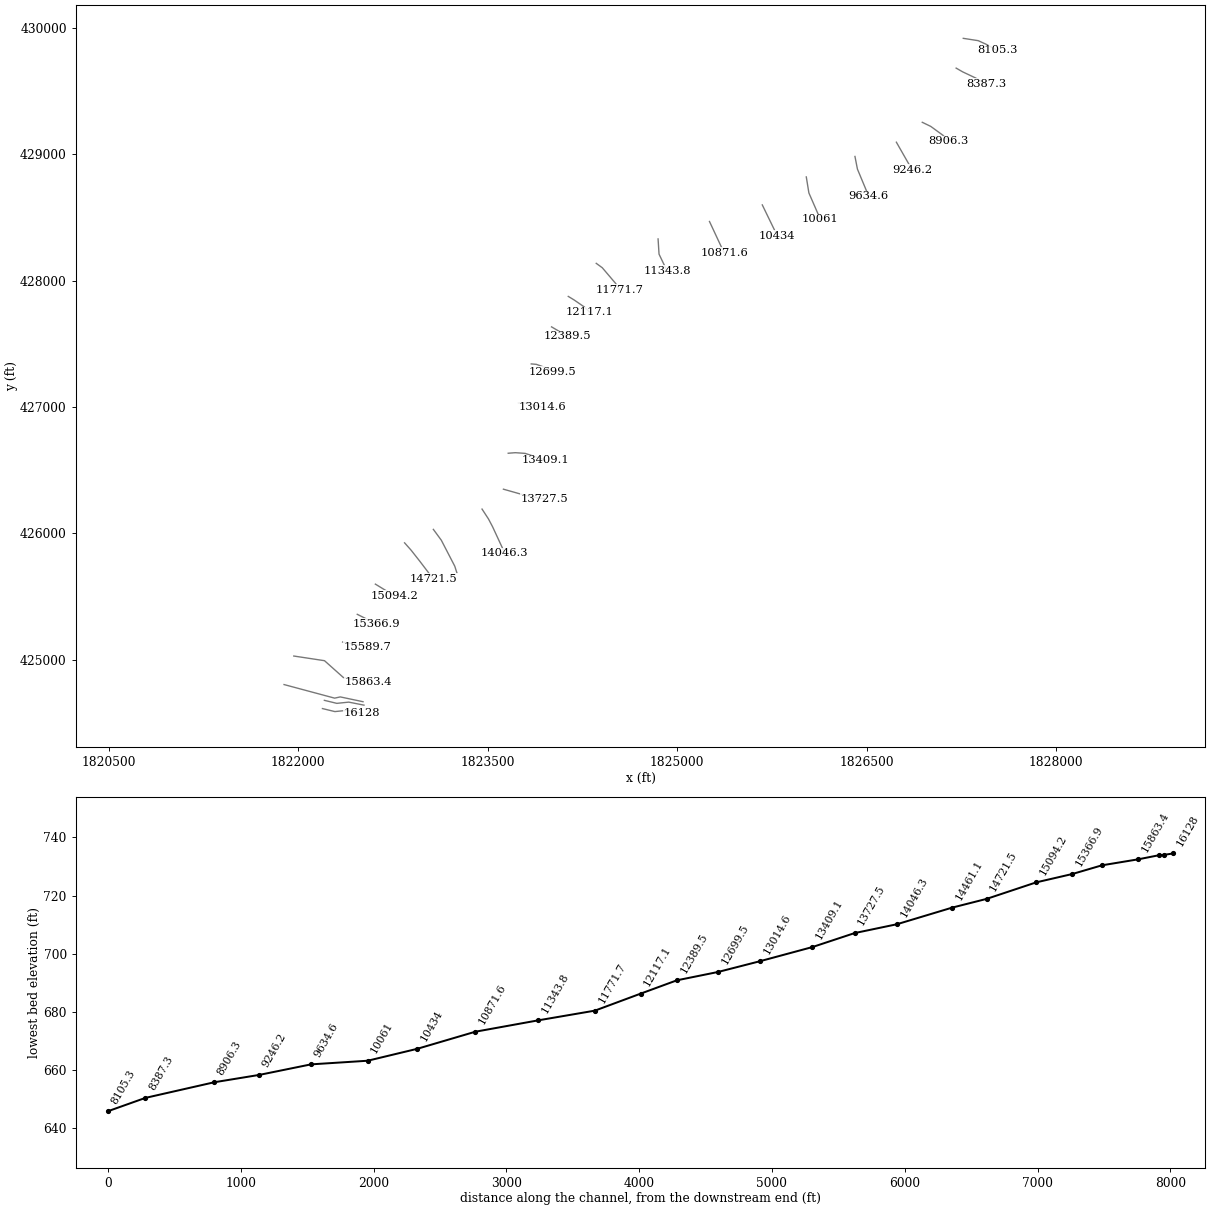
HEC-RAS study SLGHTERCK.prj: SLGHTERCK

--- SLGHTERCK.g01 (geometry) --- (continued)

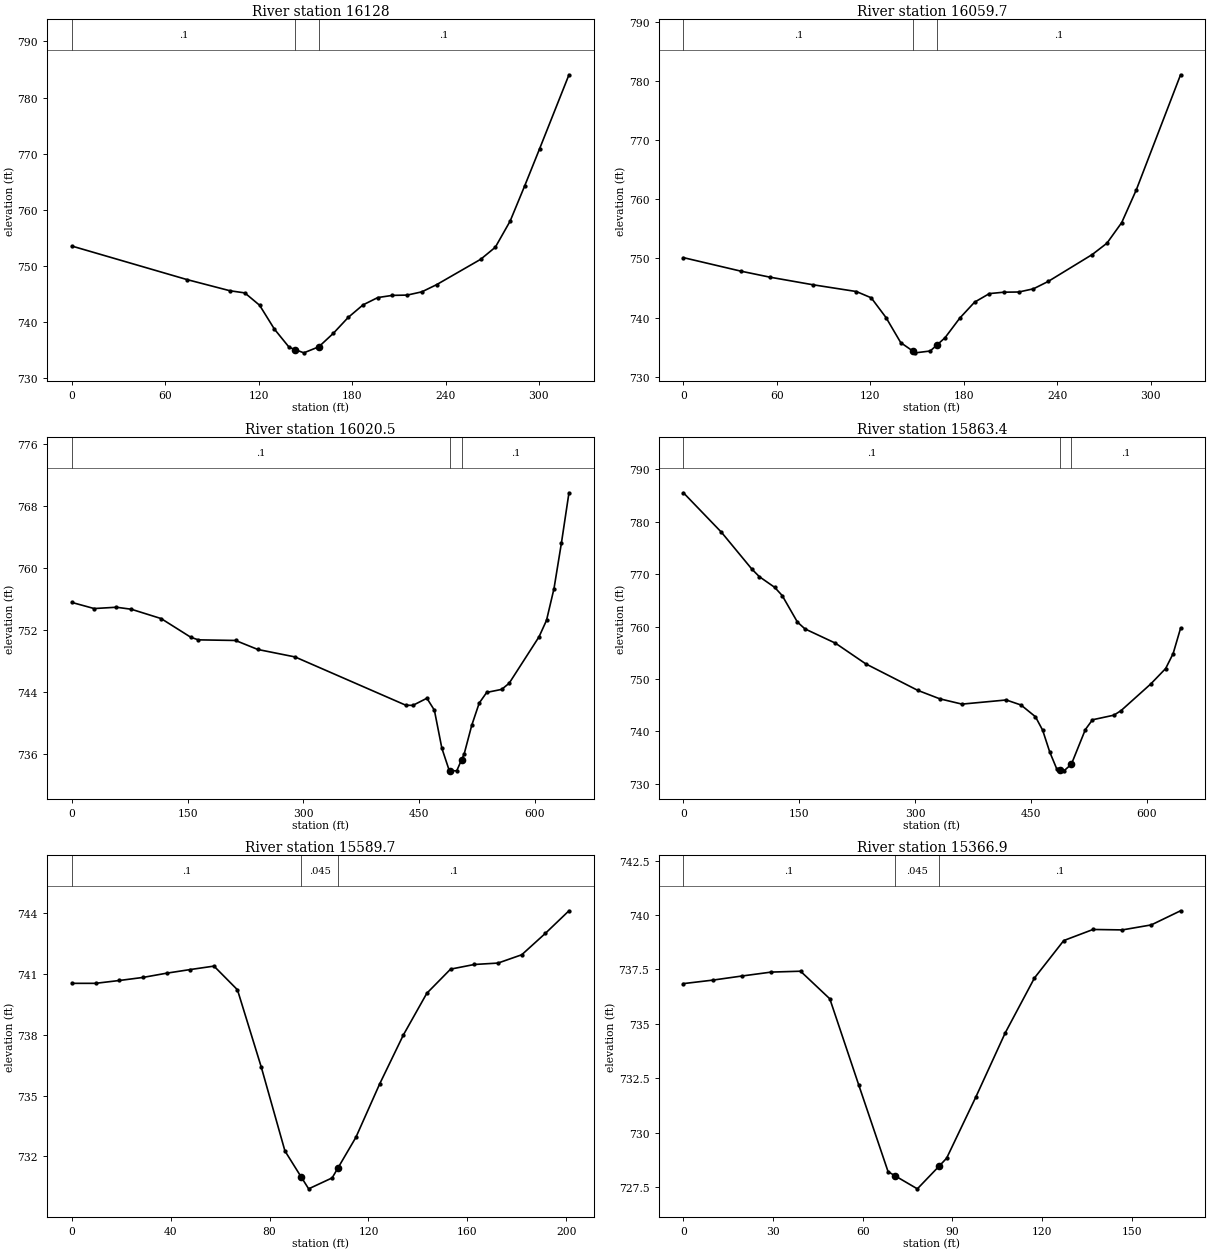
Type RM Length L Ch R = 1 ,16128   ,68.2,68.3,68.2
XS GIS Cut Line= 4
     1822192.044        424615.1     1822290.786      424591.229
     1822385.187      424600.994     1822505.629      424577.123
#Sta/Elev= 24
       0  753.53    73.9  747.56   101.6  745.56   111.1  745.18   120.6  742.98
   130.1  738.73   139.6  735.48   143.6  735.06     149   734.5   158.6  735.57
     168  737.99   177.5  740.81     187  743.04   196.5  744.35   205.9  744.74
   215.4  744.79   224.8  745.37   234.3  746.65   262.6  751.17     272  753.32
   281.5  757.97   290.9  764.28   300.4  770.84   319.3  784.05
#Mann= 3 , 0 , 0
       0      .1       0   143.6    .045       0   158.6      .1       0
Bank Sta=143.6,158.6
XS Rating Curve= 0 ,0
Exp/Cntr=0.3,0.1

Type RM Length L Ch R = 1 ,16059.7 ,47.1,39.2,32.2
XS GIS Cut Line= 4
     1822207.235      424680.204     1822305.977      424656.333
     1822400.378      424666.098      1822520.82      424642.227
#Sta/Elev= 25
       0  750.14    36.9  747.85    55.4  746.84    83.1  745.55   111.1   744.4
   120.6  743.34   130.1     740   139.6  735.74   147.7  734.26     149  734.02
   158.5  734.33   162.7  735.32     168  736.57   177.5   739.9     187   742.6
   196.5  744.05   205.9  744.29   215.4  744.32   224.8  744.86   234.3  746.11
   262.6  750.67     272  752.58   281.5  756.07   290.9  761.63   319.3   781.1
#Mann= 3 , 0 , 0
       0      .1       0   147.7    .045       0   162.7      .1       0
Bank Sta=147.7,162.7
XS Rating Curve= 0 ,0
Exp/Cntr=0.3,0.1

Type RM Length L Ch R = 1 ,16020.5 ,156.1,157.1,158.1
XS GIS Cut Line= 4
     1821888.225      424804.987     1822288.616      424697.565
     1822333.103      424707.331     1822513.225      424669.354
#Sta/Elev= 30
       0  755.58    28.9  754.79    57.8  754.96    77.1   754.7   115.7   753.5
   154.2  751.09   163.9  750.76   212.1  750.68     241  749.52   289.2  748.56
   432.8  742.34   441.9  742.32   460.1  743.24   469.8   741.7   479.5   736.8
   489.2  733.89   490.2  733.89   498.8   733.9   505.2  735.35   508.5   736.1
   518.2  739.75   527.9  742.62   537.6  743.99     557  744.38   566.7  745.17
   605.4  751.15   615.1  753.27   624.8  757.36   634.5  763.28   644.2   769.7
#Mann= 3 , 0 , 0
       0      .1       0   490.2    .045       0   505.2      .1       0
Bank Sta=490.2,505.2
XS Rating Curve= 0 ,0
Exp/Cntr=0.3,0.1

Type RM Length L Ch R = 1 ,15863.4 ,274.3,273.7,273.1
XS GIS Cut Line= 5
     1821965.265      425030.682      1822208.32      424993.789
      1822358.06      424860.326     1822476.333      424840.795
     1822551.202      424822.348
#Sta/Elev= 30
       0  785.52    49.2  777.99    88.5  770.97    98.3  769.51     118  767.49
   127.8  765.92   147.5  760.86   157.3  759.55   196.7  756.83     236  752.88
   303.2  747.83   331.8  746.21   360.5   745.2   417.8  745.99   436.9  745.03
   455.6  742.79   464.9  740.23   474.1  736.06   483.3  732.79   487.1  732.66
   492.5  732.47   502.1  733.73   520.2  740.35   529.4  742.21   557.1  743.09
   566.3  743.95   604.8  749.04   624.1  751.99   633.8  754.84   643.4  759.67
#Mann= 3 , 0 , 0
       0      .1       0   487.1    .045       0   502.1      .1       0
Bank Sta=487.1,502.1
XS Rating Curve= 0 ,0
Exp/Cntr=0.3,0.1

Type RM Length L Ch R = 1 ,15589.7 ,229,222.8,216.5
XS GIS Cut Line= 2
      1822351.55      425141.359     1822549.032      425103.381
#Sta/Elev= 24
       0  740.54     9.6  740.54    19.2  740.68    28.7  740.83    38.3  741.04
    47.9  741.22    57.5  741.39      67  740.22    76.6  736.42    86.2  732.27
    92.7     731    95.8   730.4   105.3  730.94   107.7  731.44   114.9  732.94
   124.5  735.57   134.1  737.99   143.6  740.05   153.2  741.24   162.8  741.47
   172.4  741.54     182  741.95   191.5     743   201.1  744.12
#Mann= 3 , 0 , 0
       0      .1       0    92.7    .045       0   107.7      .1       0
Bank Sta=92.7,107.7
XS Rating Curve= 0 ,0
Exp/Cntr=0.3,0.1

Type RM Length L Ch R = 1 ,15366.9 ,274.5,272.8,270.9
XS GIS Cut Line= 2
     1822467.652      425360.543     1822616.307      425285.673
#Sta/Elev= 20
       0  736.85     9.8  737.01    19.6   737.2    29.4  737.38    39.2  737.42
      49  736.15    58.7  732.18    68.5   728.2    70.7  728.02    78.3  727.41
    85.7  728.47    88.1  728.82    97.9  731.64   107.7  734.58   117.5  737.11
   127.3  738.83   137.1  739.34   146.9  739.32   156.6  739.55   166.4   740.2
#Mann= 3 , 0 , 0
       0      .1       0    70.7    .045       0    85.7      .1       0
Bank Sta=70.7,85.7
XS Rating Curve= 0 ,0
Exp/Cntr=0.3,0.1

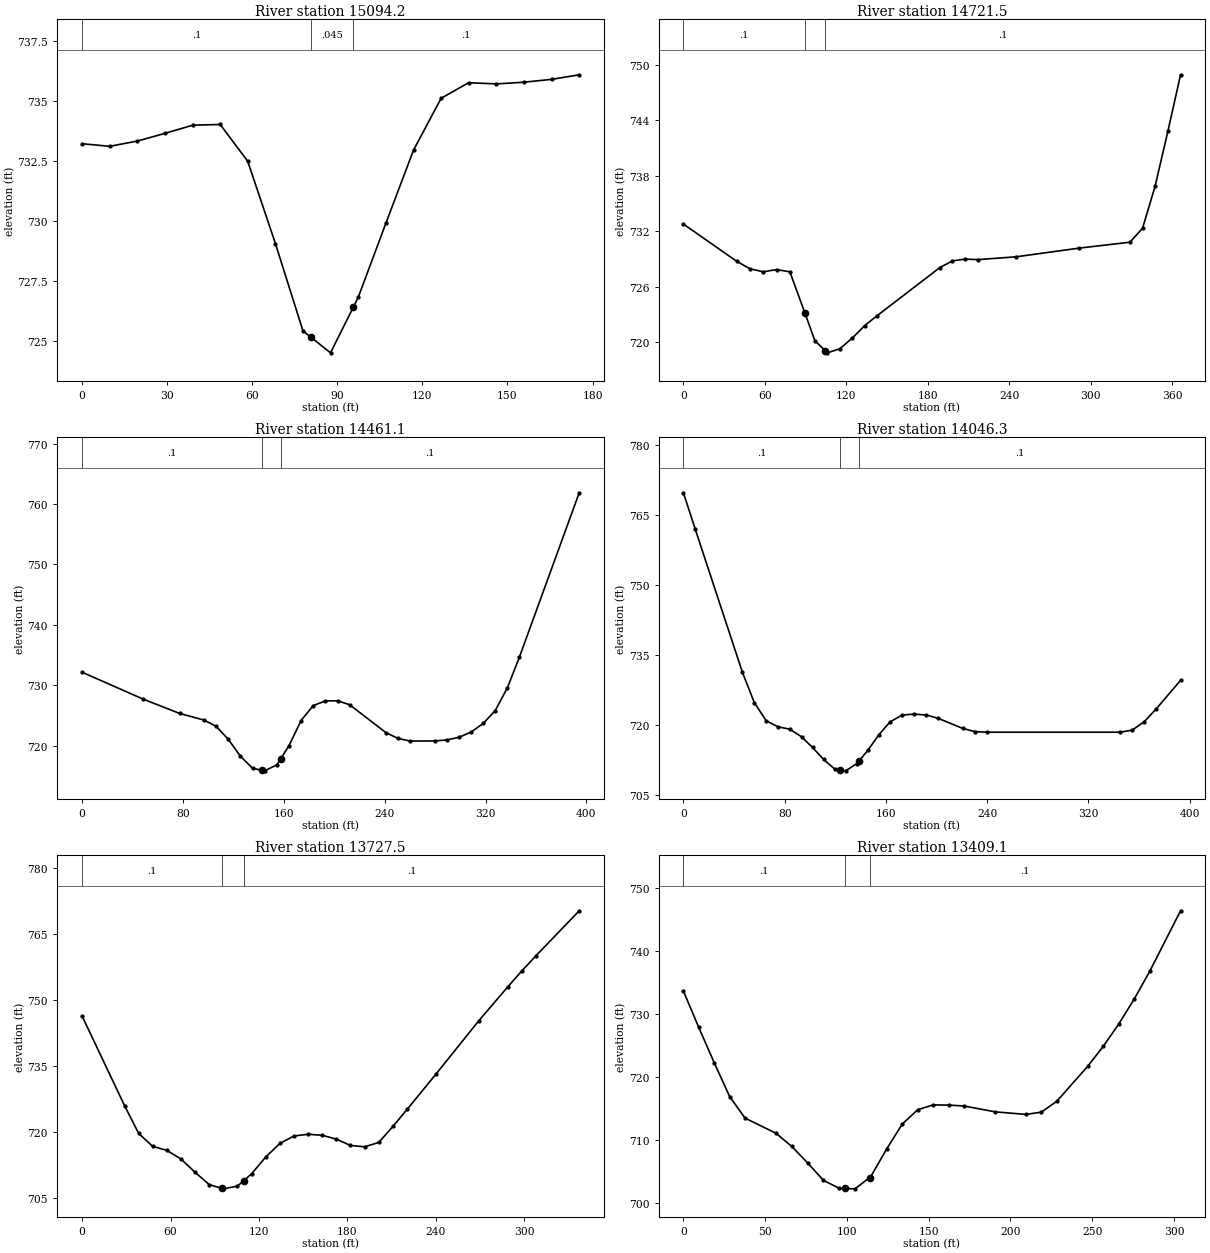
Type RM Length L Ch R = 1 ,15094.2 ,380.5,372.7,364.6
XS GIS Cut Line= 2
     1822610.881      425599.258     1822760.621      425508.112
#Sta/Elev= 21
       0  733.23     9.7  733.12    19.5  733.34    29.2  733.66      39     734
    48.7  734.03    58.4   732.5    68.2  729.06    77.9  725.43    80.6  725.18
    87.6  724.52    95.6  726.41    97.4  726.84   107.1  729.91   116.9  732.97
   126.6  735.12   136.3  735.77   146.1  735.72   155.8  735.79   165.6  735.91
   175.3   736.1
#Mann= 3 , 0 , 0
       0      .1       0    80.6    .045       0    95.6      .1       0
Bank Sta=80.6,95.6
XS Rating Curve= 0 ,0
Exp/Cntr=0.3,0.1

Type RM Length L Ch R = 1 ,14721.5 ,264.8,260.4,255.9
XS GIS Cut Line= 4
     1822842.001      425925.864     1822894.084       425867.27
     1822962.444      425780.465     1823069.866      425639.406
#Sta/Elev= 25
       0  732.76    39.2  728.74      49  727.93    58.8   727.6    68.6  727.84
    78.4   727.6    89.5  723.14    96.8  720.16   104.5  719.06     106  718.84
   115.2  719.28   124.4  720.44   133.6  721.79   142.8  722.87   188.9  728.06
   198.2  728.78   207.6  728.97   216.9  728.92   244.9  729.22   291.5  730.16
   328.9   730.8   338.2  732.31   347.5  736.88   356.9  742.82   366.2   748.9
#Mann= 3 , 0 , 0
       0      .1       0    89.5    .045       0   104.5      .1       0
Bank Sta=89.5,104.5
XS Rating Curve= 0 ,0
Exp/Cntr=0.3,0.1

Type RM Length L Ch R = 1 ,14461.1 ,414.6,414.8,414.9
XS GIS Cut Line= 4
     1823069.866      426032.201       1823132.8       425946.48
     1823239.136      425741.402     1823256.498      425687.149
#Sta/Elev= 30
       0  732.15    48.3  727.71    77.3  725.33    96.7  724.23   106.3   723.2
     116  721.03   125.6  718.24   135.2  716.24   142.4  715.92   144.8  715.82
   154.5  716.82   157.4  717.78   164.1  719.99   173.7  724.15   183.3  726.62
     193   727.4   202.6  727.42   212.2  726.77   241.1  722.13   250.7  721.18
   260.4  720.75   279.6  720.77   289.2  720.94   298.8  721.37   308.5  722.24
   318.1  723.66   327.7   725.8   337.4  729.61   346.8  734.62   394.3  761.87
#Mann= 3 , 0 , 0
       0      .1       0   142.4    .045       0   157.4      .1       0
Bank Sta=142.4,157.4
XS Rating Curve= 0 ,0
Exp/Cntr=0.3,0.1

Type RM Length L Ch R = 1 ,14046.3 ,300.4,318.8,336.9
XS GIS Cut Line= 4
     1823455.065      426192.791     1823506.064      426114.666
     1823538.616      426052.817     1823635.187      425844.484
#Sta/Elev= 30
       0  769.77     9.3  761.99    46.6  731.26      56  724.76    65.3  720.88
    74.6  719.56      84  719.05    93.3  717.42     102  715.13   110.8  712.55
   119.5  710.51   123.8  710.31   128.2  710.11     137  711.66   138.8  712.25
   145.7   714.5   154.4  717.84   163.2   720.6   172.8  722.08   182.3  722.28
   191.9  722.09   201.5  721.36   220.6  719.22   230.2  718.53   239.7   718.4
     345   718.4   354.6  718.84   364.1  720.66   373.7  723.44   392.8  729.53
#Mann= 3 , 0 , 0
       0      .1       0   123.8    .045       0   138.8      .1       0
Bank Sta=123.8,138.8
XS Rating Curve= 0 ,0
Exp/Cntr=0.3,0.1

Type RM Length L Ch R = 1 ,13727.5 ,313.5,318.4,322.8
XS GIS Cut Line= 3
     1823624.336      426350.126     1823827.244      426292.617
     1823952.099      426273.086
#Sta/Elev= 30
       0  746.37    28.8     726    38.4  719.66    47.9  716.72    57.5  715.81
    67.1  713.85    76.7   710.8    86.3  708.02    94.6  707.19    95.9  707.06
   105.4  707.68   109.6   708.9     115  710.48   124.6   714.3   134.2  717.39
   143.8  719.09   153.4  719.47     163  719.24   172.6  718.36   182.1  716.93
   191.7  716.62   201.3  717.62   210.9  721.26   220.6  725.16   240.1  733.16
   269.2  745.32   288.7  752.96   298.4  756.65   308.1  760.14   337.3  770.32
#Mann= 3 , 0 , 0
       0      .1       0    94.6    .045       0   109.6      .1       0
Bank Sta=94.6,109.6
XS Rating Curve= 0 ,0
Exp/Cntr=0.3,0.1

Type RM Length L Ch R = 1 ,13409.1 ,398.6,394.5,390.3
XS GIS Cut Line= 4
     1823662.314      426634.414     1823718.737      426638.755
     1823795.777      426633.329     1823957.452      426580.161
#Sta/Elev= 30
       0  733.66     9.4  727.89    18.9  722.24    28.3  716.89    37.7  713.48
    56.6  711.08    66.2  708.99    75.9  706.38    85.6  703.59    95.2  702.34
    98.8   702.3   104.9  702.24   113.8  704.02   114.5  704.16   124.2  708.54
   133.8  712.53   143.3  714.82   152.7  715.58   162.2  715.55   171.6  715.41
   190.6  714.48   209.5  714.07   218.9  714.43   228.4  716.18   247.3  721.75
   256.7  724.88   266.2  728.44   275.6  732.38   285.1  736.79     304  746.44
#Mann= 3 , 0 , 0
       0      .1       0    98.8    .045       0   113.8      .1       0
Bank Sta=98.8,113.8
XS Rating Curve= 0 ,0
Exp/Cntr=0.3,0.1

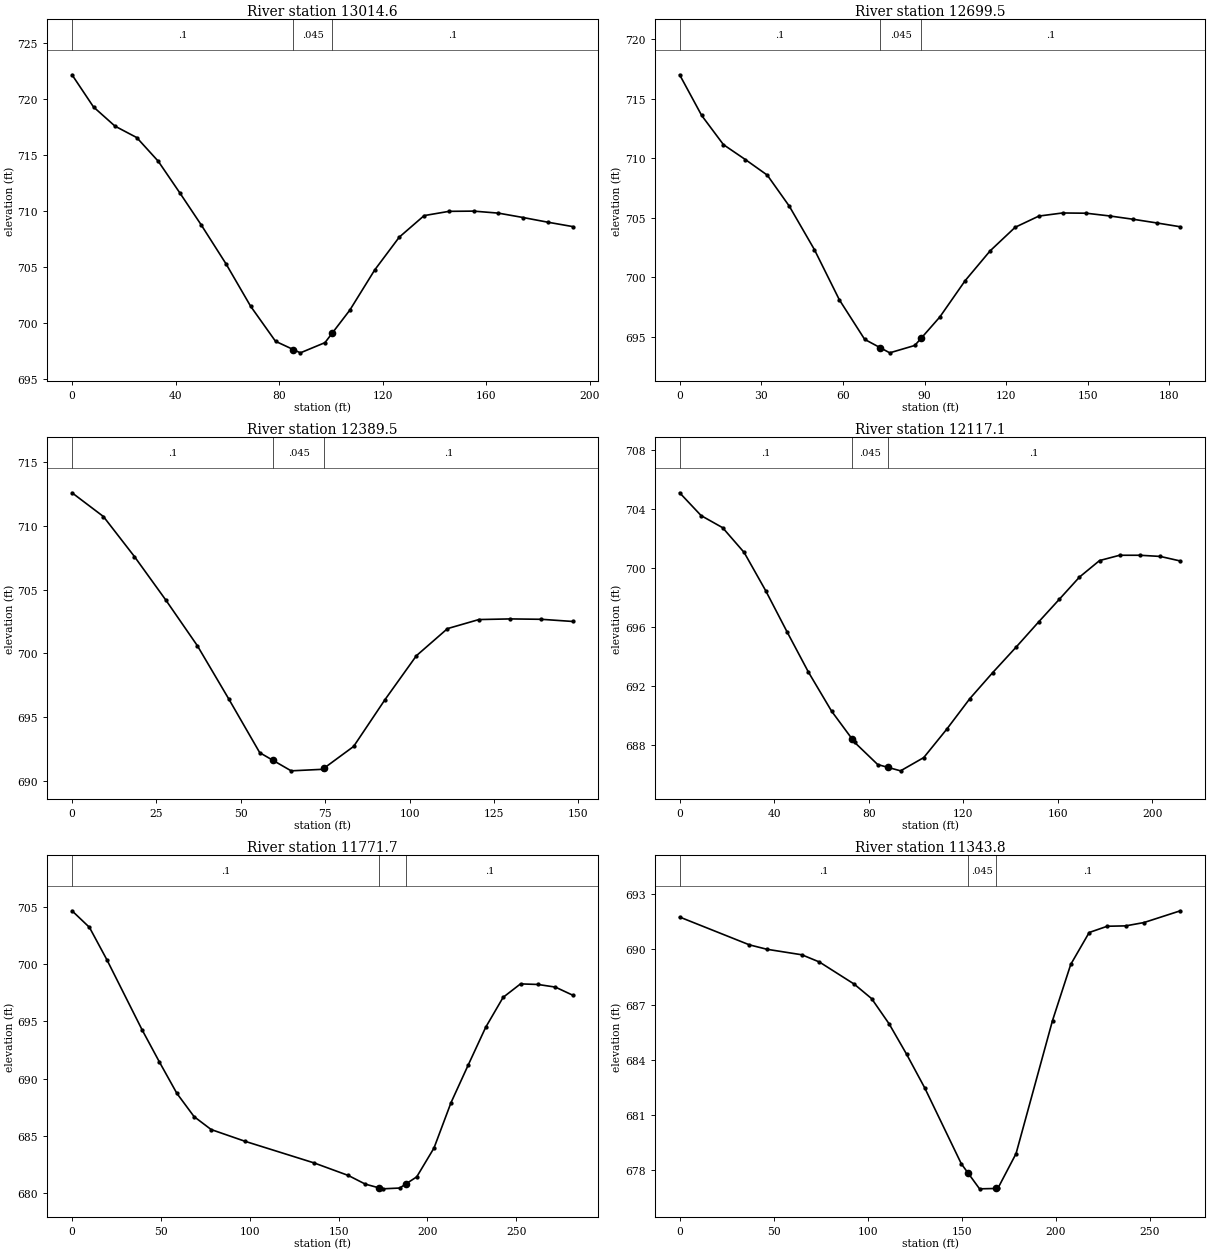
Type RM Length L Ch R = 1 ,13014.6 ,317.1,315,312.8
XS GIS Cut Line= 3
     1823744.779       427031.55     1823794.692      427032.635
     1823933.581      426996.827
#Sta/Elev= 24
       0  722.17     8.3   719.3    16.6  717.59      25  716.57    33.3  714.46
    41.6  711.65    49.9  708.78    59.5   705.3      69  701.52    78.6   698.4
    85.5  697.66    88.2  697.37    97.7  698.28   100.5  699.13   107.3  701.18
   116.9  704.76   126.4  707.69     136  709.61   145.6  709.99   155.1  710.01
   164.7  709.83   174.2  709.44   183.8  709.02   193.4  708.63
#Mann= 3 , 0 , 0
       0      .1       0    85.5    .045       0   100.5      .1       0
Bank Sta=85.5,100.5
XS Rating Curve= 0 ,0
Exp/Cntr=0.3,0.1

Type RM Length L Ch R = 1 ,12699.5 ,314.1,310,305.9
XS GIS Cut Line= 4
     1823844.605      427340.795     1823884.753      427337.539
     1823962.878      427309.327     1824016.046      427280.031
#Sta/Elev= 24
       0  717.03     8.1  713.61    16.1  711.16    24.2   709.9    32.2   708.6
    40.3  705.99    49.5  702.35    58.7  698.12      68   694.8    73.8  694.09
    77.2  693.67    86.4  694.29    88.8  694.91    95.6  696.68   104.9  699.73
   114.1  702.24   123.3  704.22     132  705.16   140.7  705.42   149.4   705.4
     158  705.17   166.7  704.89   175.4  704.58     184  704.26
#Mann= 3 , 0 , 0
       0      .1       0    73.8    .045       0    88.8      .1       0
Bank Sta=73.8,88.8
XS Rating Curve= 0 ,0
Exp/Cntr=0.3,0.1

Type RM Length L Ch R = 1 ,12389.5 ,274,272.4,270.6
XS GIS Cut Line= 2
     1824005.195      427633.763     1824133.234      427558.893
#Sta/Elev= 19
       0  712.58     9.3  710.72    18.5  707.58    27.8  704.17    37.1  700.61
    46.4  696.44    55.6  692.22    59.6  691.61    64.9   690.8    74.2  690.92
    74.6     691    83.4  692.71    92.7  696.38     102  699.82   111.2  701.94
   120.5  702.65   129.8   702.7     139  702.67   148.3   702.5
#Mann= 3 , 0 , 0
       0      .1       0    59.6    .045       0    74.6      .1       0
Bank Sta=59.6,74.6
XS Rating Curve= 0 ,0
Exp/Cntr=0.3,0.1

Type RM Length L Ch R = 1 ,12117.1 ,348.6,345.4,340.1
XS GIS Cut Line= 4
     1824137.574      427874.649     1824184.232      427846.437
     1824264.527      427791.098      1824307.93      427749.866
#Sta/Elev= 26
       0  705.09     9.1  703.54    18.2  702.72    27.3  701.04    36.4  698.45
    45.4  695.67    54.5  692.92    64.3  690.27      73  688.38      74  688.16
    83.8  686.65      88  686.46    93.5  686.22   103.3  687.12     113  689.04
   122.8  691.12   132.5  692.89   142.3   694.6     152  696.34   160.6  697.85
   169.2  699.37   177.7  700.49   186.2  700.85   194.8  700.85   203.4  700.77
   211.9  700.46
#Mann= 3 , 0 , 0
       0      .1       0      73    .045       0      88      .1       0
Bank Sta=73,88
XS Rating Curve= 0 ,0
Exp/Cntr=0.3,0.1

Type RM Length L Ch R = 1 ,11771.7 ,436.1,427.9,421.2
XS GIS Cut Line= 4
     1824358.928       428136.15     1824406.671      428101.428
     1824513.008      427976.645     1824542.305      427925.647
#Sta/Elev= 26
       0  704.69     9.8  703.24    19.7  700.38    39.4  694.28    49.2  691.45
      59  688.71    68.7  686.67    78.3  685.54    97.6   684.5   136.2  682.62
   155.5  681.52   165.1  680.76   172.9  680.43   174.8  680.35   184.4  680.42
   187.9  680.78     194   681.4   203.7  683.92   213.3   687.9     223   691.2
   232.8  694.49   242.6  697.11   252.4  698.29   262.2  698.24     272  698.01
   281.8   697.3
#Mann= 3 , 0 , 0
       0      .1       0   172.9    .045       0   187.9      .1       0
Bank Sta=172.9,187.9
XS Rating Curve= 0 ,0
Exp/Cntr=0.3,0.1

Type RM Length L Ch R = 1 ,11343.8 ,472.2,472.2,471.7
XS GIS Cut Line= 3
     1824848.294      428329.293      1824855.89       428208.85
     1824918.824      428077.557
#Sta/Elev= 23
       0  691.76    37.1  690.25    46.4  690.01      65  689.71    74.3  689.32
    92.8  688.12   102.1  687.33   111.4  685.96   120.7  684.31   130.4  682.47
   149.8  678.36   153.3  677.87   159.5     677   168.3  677.02   169.2  677.02
   178.9  678.91   198.3  686.14     208  689.19   217.8  690.92   227.4  691.26
   237.2  691.28   246.9  691.46   266.3   692.1
#Mann= 3 , 0 , 0
       0      .1       0   153.3    .045       0   168.3      .1       0
Bank Sta=153.3,168.3
XS Rating Curve= 0 ,0
Exp/Cntr=0.3,0.1

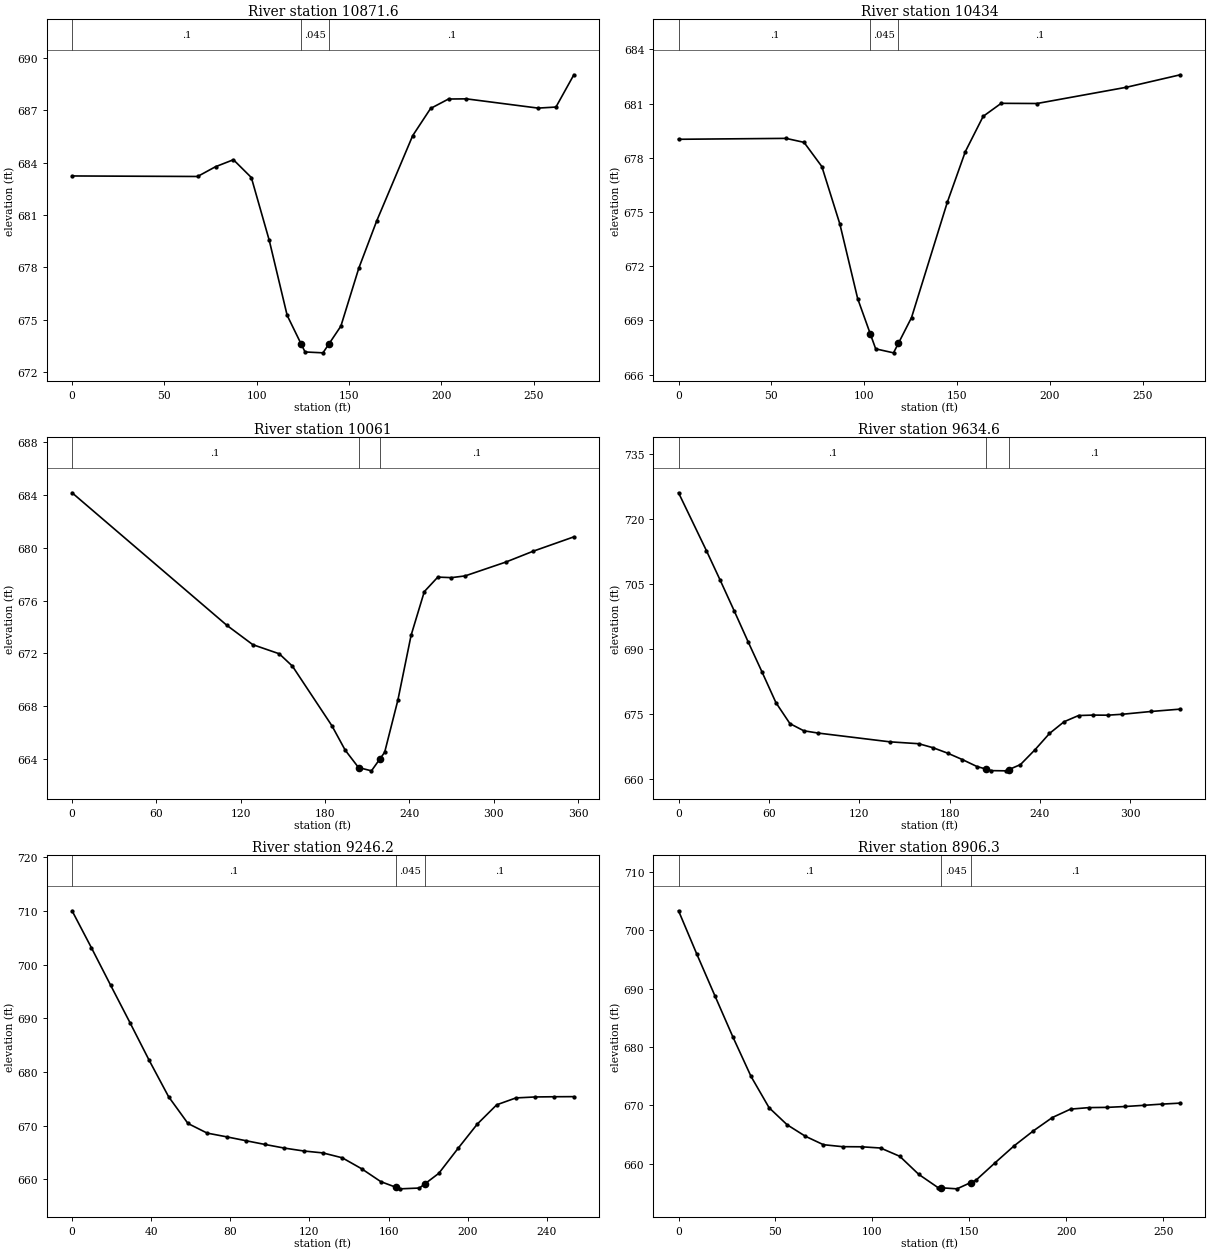
Type RM Length L Ch R = 1 ,10871.6 ,437.2,437.7,437.9
XS GIS Cut Line= 2
     1825255.195      428467.097     1825370.213      428220.786
#Sta/Elev= 21
       0  683.23      68   683.2    77.7  683.76    87.4  684.16    97.1  683.14
   106.8  679.54   116.5  675.24   124.2  673.57   126.2  673.14   135.9  673.09
   139.2  673.61   145.6  674.62   155.3  677.94     165  680.65   184.5  685.54
   194.2   687.1   203.9  687.64   213.6  687.65   252.4  687.12   262.1  687.18
   271.8  689.03
#Mann= 3 , 0 , 0
       0      .1       0   124.2    .045       0   139.2      .1       0
Bank Sta=124.2,139.2
XS Rating Curve= 0 ,0
Exp/Cntr=0.3,0.1

Type RM Length L Ch R = 1 ,10434   ,374,372.9,372.1
XS GIS Cut Line= 2
     1825672.947       428598.39      1825791.22      428355.334
#Sta/Elev= 18
       0  679.02    57.9  679.07    67.6  678.85    77.2  677.51    86.9  674.33
    96.5   670.2   103.4  668.22   106.2  667.42   115.8   667.2   118.4  667.72
   125.5  669.15   144.8  675.54   154.5  678.34   164.1  680.29   173.8  681.01
   193.1     681   241.3   681.9   270.3  682.59
#Mann= 3 , 0 , 0
       0      .1       0   103.4    .045       0   118.4      .1       0
Bank Sta=103.4,118.4
XS Rating Curve= 0 ,0
Exp/Cntr=0.3,0.1

Type RM Length L Ch R = 1 ,10061   ,426.8,426.4,426
XS GIS Cut Line= 4
     1826021.254      428819.744     1826041.871      428692.791
     1826090.699      428581.029     1826133.017      428483.373
#Sta/Elev= 20
       0  684.17   110.2  674.12   128.6  672.66   147.4  671.97   156.8  671.03
   184.9  666.51   194.3  664.67   203.8  663.35     213   663.1   218.8  663.97
   222.4  664.51   231.8  668.46   241.2  673.37   250.6  676.68   260.2  677.78
   269.9  677.74   279.6  677.87   308.6  678.92     328  679.74     357  680.83
#Mann= 3 , 0 , 0
       0      .1       0   203.8    .045       0   218.8      .1       0
Bank Sta=203.8,218.8
XS Rating Curve= 0 ,0
Exp/Cntr=0.3,0.1

Type RM Length L Ch R = 1 ,9634.6  ,385.6,388.4,391.2
XS GIS Cut Line= 3
     1826406.454       428981.42     1826425.985      428881.593
     1826514.961      428667.834
#Sta/Elev= 30
       0  726.05    18.5   712.7    27.7  705.84      37  698.77    46.2  691.66
    55.5  684.64    64.7  677.59      74  672.75    83.2   671.1    92.5  670.58
   140.3  668.55   159.6  668.11   169.2  667.17   178.9  665.91   188.6  664.44
   198.2  662.85   204.4  662.24   207.8   661.9   217.5  661.85   219.4  662.14
   227.1  663.29   236.8  666.73   246.4  670.48   256.1  673.19   265.7  674.62
   275.4  674.72     285   674.7   294.7  674.91     314  675.56   333.3   676.1
#Mann= 3 , 0 , 0
       0      .1       0   204.4    .045       0   219.4      .1       0
Bank Sta=204.4,219.4
XS Rating Curve= 0 ,0
Exp/Cntr=0.3,0.1

Type RM Length L Ch R = 1 ,9246.2  ,330.2,339.9,349.3
XS GIS Cut Line= 2
     1826734.145      429094.267     1826860.013      428873.998
#Sta/Elev= 29
       0  710.01     9.8  703.11    19.5  696.14    29.3  689.16      39  682.15
    48.8  675.39    58.6   670.4    68.3  668.61    78.1  667.92    87.8   667.2
    97.6  666.49   107.3  665.82   117.1  665.28   126.8  664.92   136.6  664.01
   146.4  661.97   156.1  659.57   163.6  658.54   165.9  658.23   175.6  658.38
   178.6  659.22   185.4  661.11   195.2  665.79   204.9   670.3   214.7  673.88
   224.4  675.16   234.2  675.34   243.9  675.38   253.7   675.4
#Mann= 3 , 0 , 0
       0      .1       0   163.6    .045       0   178.6      .1       0
Bank Sta=163.6,178.6
XS Rating Curve= 0 ,0
Exp/Cntr=0.3,0.1

Type RM Length L Ch R = 1 ,8906.3  ,514.7,519,523
XS GIS Cut Line= 4
     1826939.223      429251.602     1827006.498       429219.05
     1827101.984      429149.605     1827148.642      429102.947
#Sta/Elev= 30
       0  703.37     9.3  696.04    18.7  688.84      28  681.76    37.4  674.96
    46.7   669.6      56  666.68    65.4  664.71    74.7  663.26    84.6  662.92
    94.4   662.9   104.2  662.69   114.1  661.27   123.9  658.17   133.8  655.91
   135.6  655.87   143.6  655.69   150.6  656.75   153.4  657.17   163.3  660.17
   173.1  663.07     183  665.63   192.8  667.92   202.2  669.36   211.7  669.62
   221.1  669.66   230.5  669.81   239.9  670.01   249.4  670.22   258.8  670.39
#Mann= 3 , 0 , 0
       0      .1       0   135.6    .045       0   150.6      .1       0
Bank Sta=135.6,150.6
XS Rating Curve= 0 ,0
Exp/Cntr=0.3,0.1

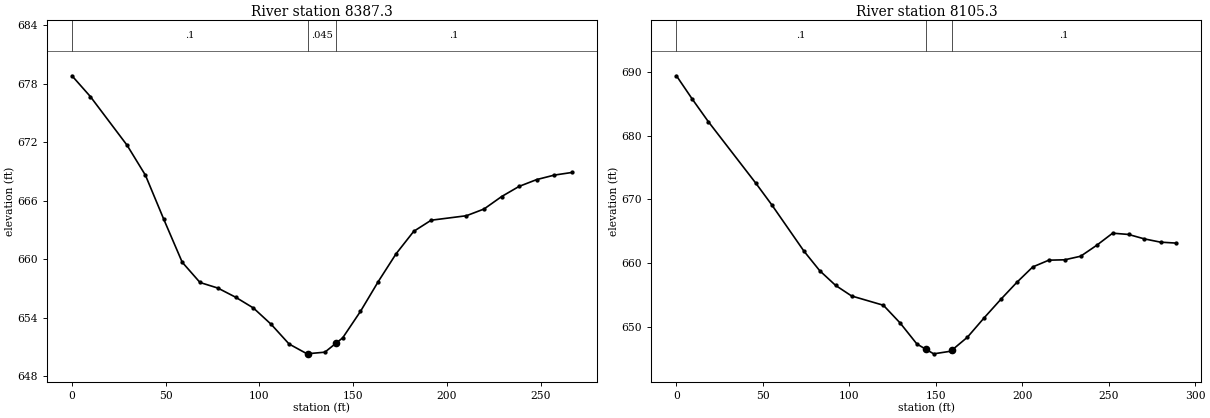
Type RM Length L Ch R = 1 ,8387.3  ,281.2,282,281.9
XS GIS Cut Line= 4
     1827207.235      429680.204     1827258.234      429650.907
     1827361.315      429602.079     1827442.695      429555.421
#Sta/Elev= 29
       0  678.83     9.8   676.7    29.4   671.7    39.2  668.62      49  664.09
    58.8   659.7    68.3  657.62    77.8  657.05    87.3  656.11    96.8     655
   106.3  653.32   115.8  651.31   125.4   650.3   125.7  650.31   134.9  650.47
   140.7  651.37   144.4  651.94   153.9  654.66   163.4  657.72   172.9  660.57
   182.3  662.87   191.6  664.01   210.4  664.47   219.8  665.16   229.2  666.44
   238.5  667.48   247.9  668.18   257.3  668.64   266.7  668.91
#Mann= 3 , 0 , 0
       0      .1       0   125.7    .045       0   140.7      .1       0
Bank Sta=125.7,140.7
XS Rating Curve= 0 ,0
Exp/Cntr=0.3,0.1

Type RM Length L Ch R = 1 ,8105.3  ,271.7,287.2,301.9
XS GIS Cut Line= 4
     1827263.659      429915.664     1827381.932      429897.218
     1827443.781      429869.006     1827532.756      429820.178
#Sta/Elev= 30
       0  689.38     9.2   685.7    18.4  682.19      46  672.48    55.2  669.09
    73.7  661.86    82.9  658.76    92.1  656.45   101.3   654.8   119.7  653.34
   129.4  650.55   139.1  647.25   144.4  646.41   148.8  645.71   158.6  646.12
   159.4   646.3   168.3  648.32     178  651.37   187.7  654.29   196.9  656.94
   206.1  659.36   215.4  660.42   224.6  660.48   233.8  661.04     243  662.74
   252.3  664.66   261.5  664.46   270.7  663.76     280  663.25   289.2   663.1
#Mann= 3 , 0 , 0
       0      .1       0   144.4    .045       0   159.4      .1       0
Bank Sta=144.4,159.4
XS Rating Curve= 0 ,0
Exp/Cntr=0.3,0.1