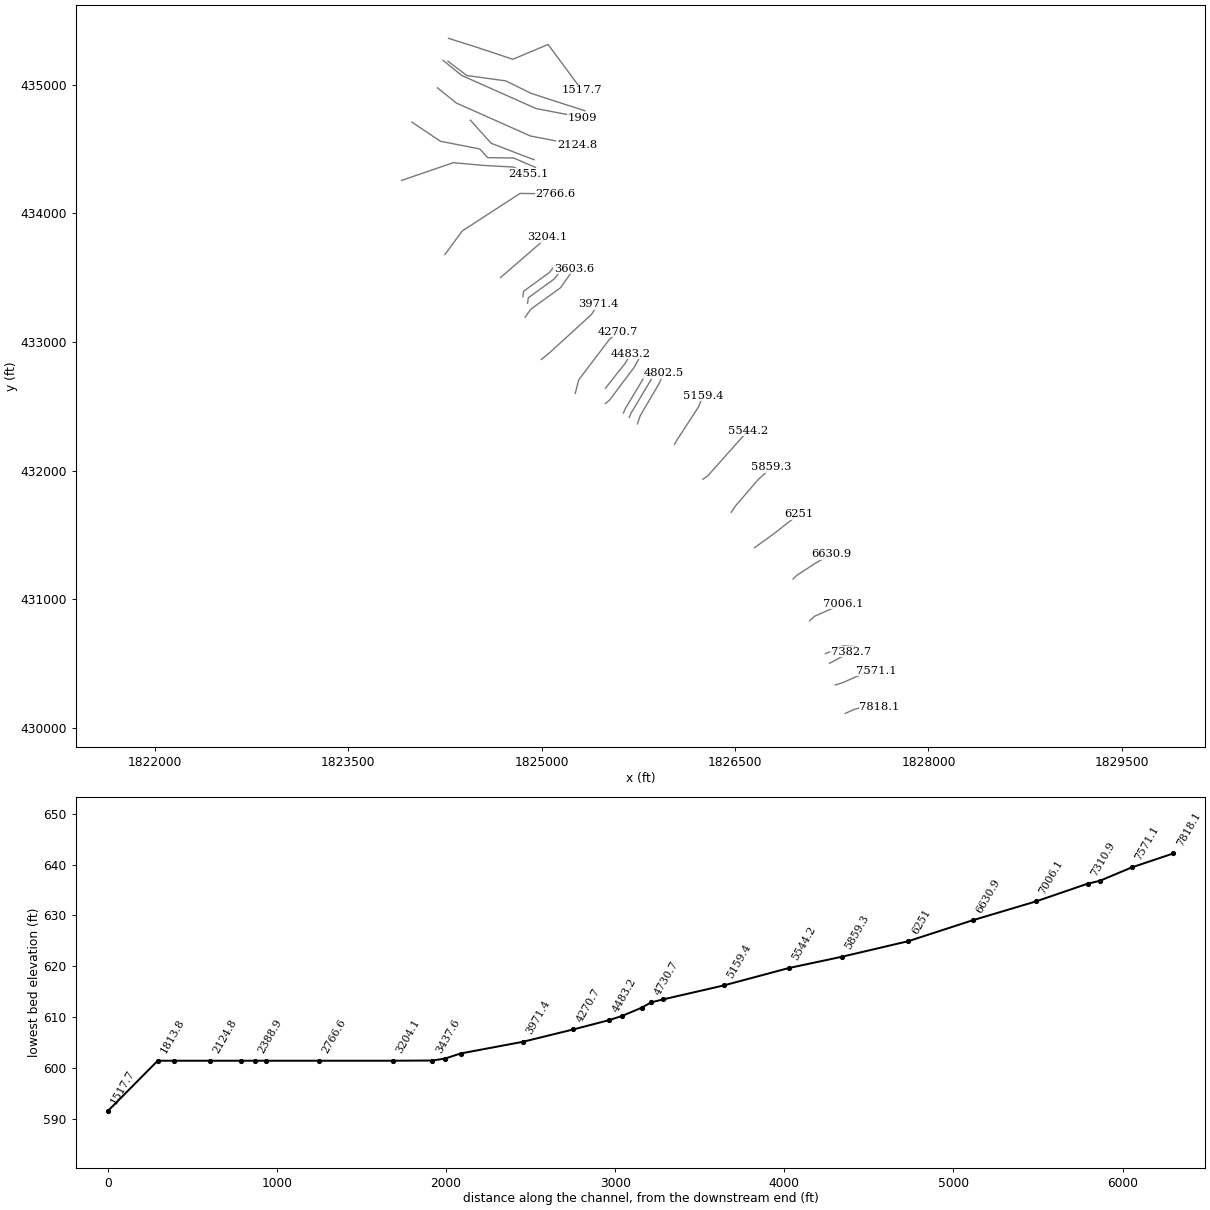
HEC-RAS study SLGHTERCK.prj: SLGHTERCK

--- SLGHTERCK.g01 (geometry) --- (continued)

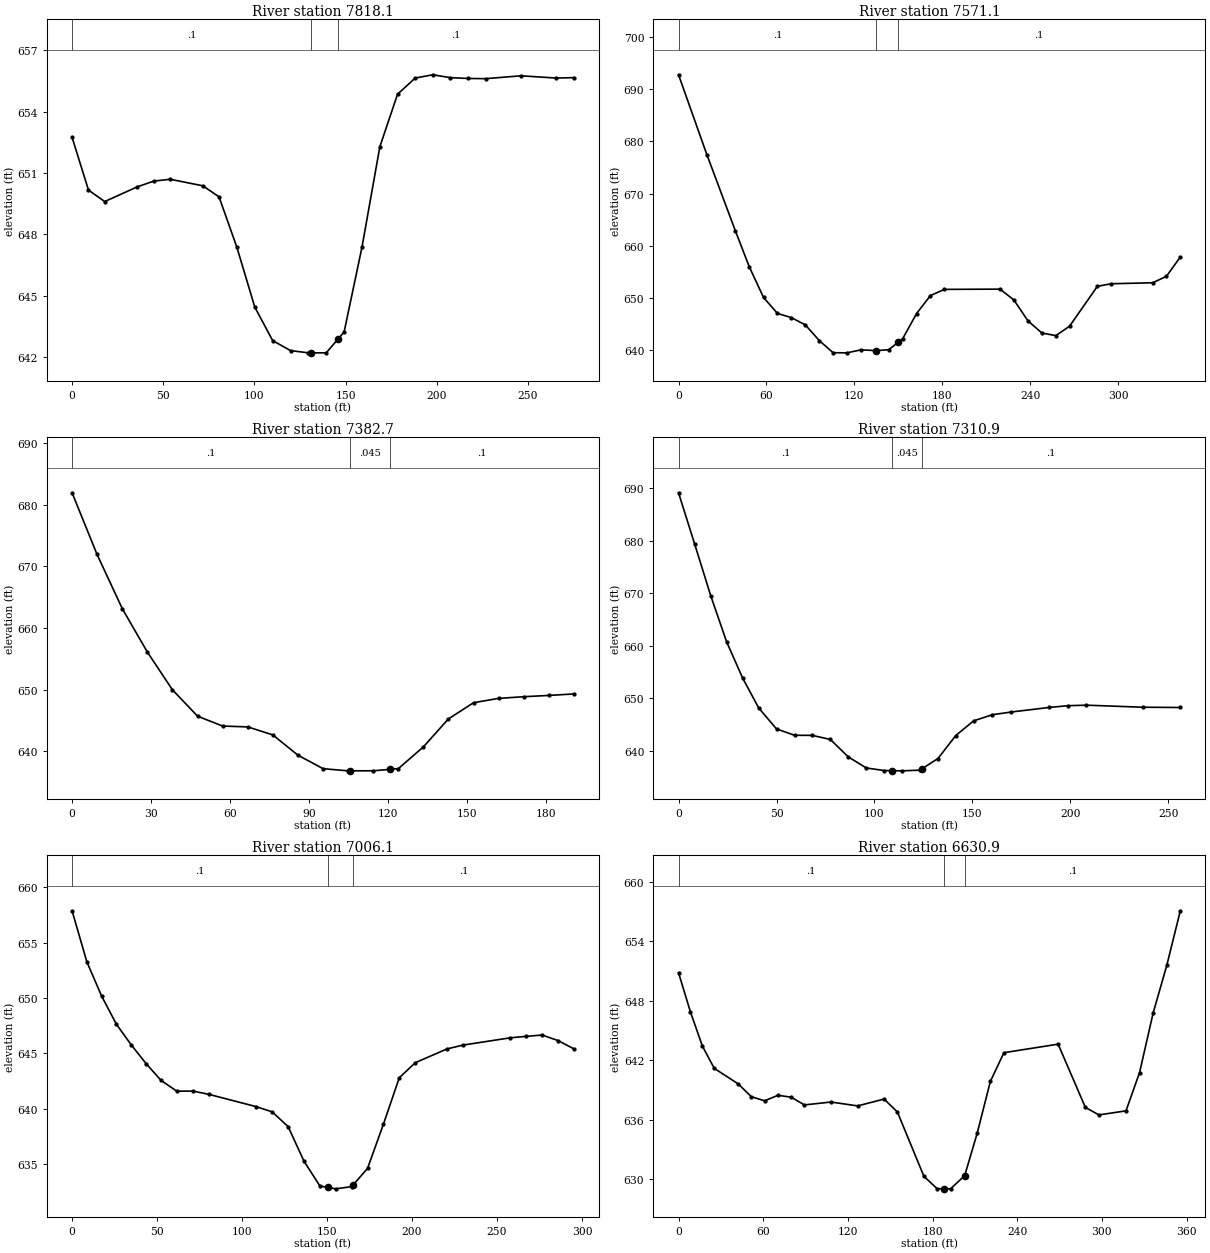
Type RM Length L Ch R = 1 ,7818.1  ,243.2,247,251.1
XS GIS Cut Line= 4
     1827354.805      430113.147      1827428.59      430145.699
      1827514.31      430166.315     1827620.647      430164.145
#Sta/Elev= 28
       0  652.74       9  650.16    17.9   649.6    35.8  650.32    44.8   650.6
    53.8  650.69    71.7  650.37    80.6  649.83    90.4  647.36   100.2  644.44
     110   642.8   119.8  642.31   129.6   642.2   131.1   642.2   139.4   642.2
   146.1   642.9   149.2  643.22     159  647.37   168.8  652.28   178.5  654.85
   188.2  655.64   197.8   655.8   207.5  655.66   217.2  655.62   226.8  655.61
   246.2  655.75   265.5  655.64   275.2  655.66
#Mann= 3 , 0 , 0
       0      .1       0   131.1    .045       0   146.1      .1       0
Bank Sta=131.1,146.1
XS Rating Curve= 0 ,0
Exp/Cntr=0.3,0.1

Type RM Length L Ch R = 1 ,7571.1  ,186.4,188.4,190.1
XS GIS Cut Line= 4
      1827276.68      430333.416     1827332.018      430350.777
     1827540.352      430443.008     1827596.775      430446.263
#Sta/Elev= 30
       0  692.77    19.3  677.48    38.7   662.9    48.3  655.92      58  650.06
    67.5     647      77  646.19    86.5  644.81      96   641.8   105.5  639.46
     115  639.44   124.4  640.01   134.9  639.87   143.4  640.04   149.9  641.46
   152.9  642.12   162.4  646.97   171.9  650.43   181.4  651.61   219.4  651.66
   228.9  649.56   238.4  645.58   247.9  643.25   257.4  642.74   266.8  644.54
   285.8   652.2   295.2  652.69   323.5  652.88   332.9  654.11   342.4  657.82
#Mann= 3 , 0 , 0
       0      .1       0   134.9    .045       0   149.9      .1       0
Bank Sta=134.9,149.9
XS Rating Curve= 0 ,0
Exp/Cntr=0.3,0.1

Type RM Length L Ch R = 1 ,7382.7  ,73.5,71.9,70.3
XS GIS Cut Line= 2
     1827232.915        430502.6      1827400.45      430593.746
#Sta/Elev= 23
       0  681.93     9.5  671.92    19.1  663.11    28.6  656.09    38.1  649.97
    47.7  645.67    57.2  644.07    66.8  643.93    76.3  642.63    85.8  639.35
    95.4  637.15   104.9   636.8   105.8   636.8   114.4  636.81   120.8  637.04
     124  637.16   133.5  640.68     143  645.22   152.6  647.86   162.1  648.56
   171.6  648.83   181.2  649.04   190.7  649.28
#Mann= 3 , 0 , 0
       0      .1       0   105.8    .045       0   120.8      .1       0
Bank Sta=105.8,120.8
XS Rating Curve= 0 ,0
Exp/Cntr=0.3,0.1

Type RM Length L Ch R = 1 ,7310.9  ,304.9,304.7,304.5
XS GIS Cut Line= 4
     1827200.725      430577.557     1827238.702      430592.748
     1827338.529      430638.321     1827443.781       430631.81
#Sta/Elev= 27
       0  689.09     8.2  679.38    16.4  669.56    24.5   660.8    32.7  653.89
    40.9   648.2      50  644.21    59.2     643    68.3  642.98    77.5   642.2
    86.6   638.9    95.8  636.79   104.9   636.3   109.2  636.27   114.1  636.24
   123.2  636.37   124.2  636.61   132.4  638.58   141.5  642.95   150.6  645.74
   160.2  646.91   169.8  647.42     189  648.28   198.6  648.62   208.2  648.72
   236.9  648.33   256.1  648.28
#Mann= 3 , 0 , 0
       0      .1       0   109.2    .045       0   124.2      .1       0
Bank Sta=109.2,124.2
XS Rating Curve= 0 ,0
Exp/Cntr=0.3,0.1

Type RM Length L Ch R = 1 ,7006.1  ,371.6,375.2,378.8
XS GIS Cut Line= 4
     1827078.112      430833.633     1827117.175      430868.355
     1827253.893      430929.119     1827339.614      430966.012
#Sta/Elev= 30
       0  657.87     8.7  653.26    17.4  650.16    26.1  647.62    34.8  645.76
    43.6  644.06    52.3  642.56    61.6  641.58      71  641.59    80.3   641.3
   108.4  640.18   117.7  639.71   127.1  638.38   136.4  635.27   145.8  633.02
   150.5  632.89   155.1  632.76   164.5  632.96   165.5  633.14   173.8   634.6
   183.2  638.61   192.5  642.79   201.9  644.15   220.5  645.39   229.9  645.74
   257.9   646.4   267.2  646.53   276.5  646.65   285.9  646.15   295.2   645.4
#Mann= 3 , 0 , 0
       0      .1       0   150.5    .045       0   165.5      .1       0
Bank Sta=150.5,165.5
XS Rating Curve= 0 ,0
Exp/Cntr=0.3,0.1

Type RM Length L Ch R = 1 ,6630.9  ,377.7,379.8,382
XS GIS Cut Line= 4
     1826950.074      431158.069     1826980.456      431187.366
     1827130.195      431285.022     1827247.383      431351.211
#Sta/Elev= 30
       0  650.85     8.4  646.91    16.9  643.45    25.3   641.2    42.2  639.64
    51.6  638.34      61  637.92    70.4  638.48    79.8  638.29    89.2  637.51
   108.1   637.8   126.9  637.41   145.7   638.1   155.1  636.79   173.9   630.3
   183.3  629.05   187.8  629.05   192.8  629.04   202.8  630.38   211.6  634.63
     221  639.89   230.6  642.78     269  643.64   288.3  637.26   297.9   636.5
   317.1  636.91   326.7  640.77   336.3  646.76     346  651.59   355.6   657.1
#Mann= 3 , 0 , 0
       0      .1       0   187.8    .045       0   202.8      .1       0
Bank Sta=187.8,202.8
XS Rating Curve= 0 ,0
Exp/Cntr=0.3,0.1

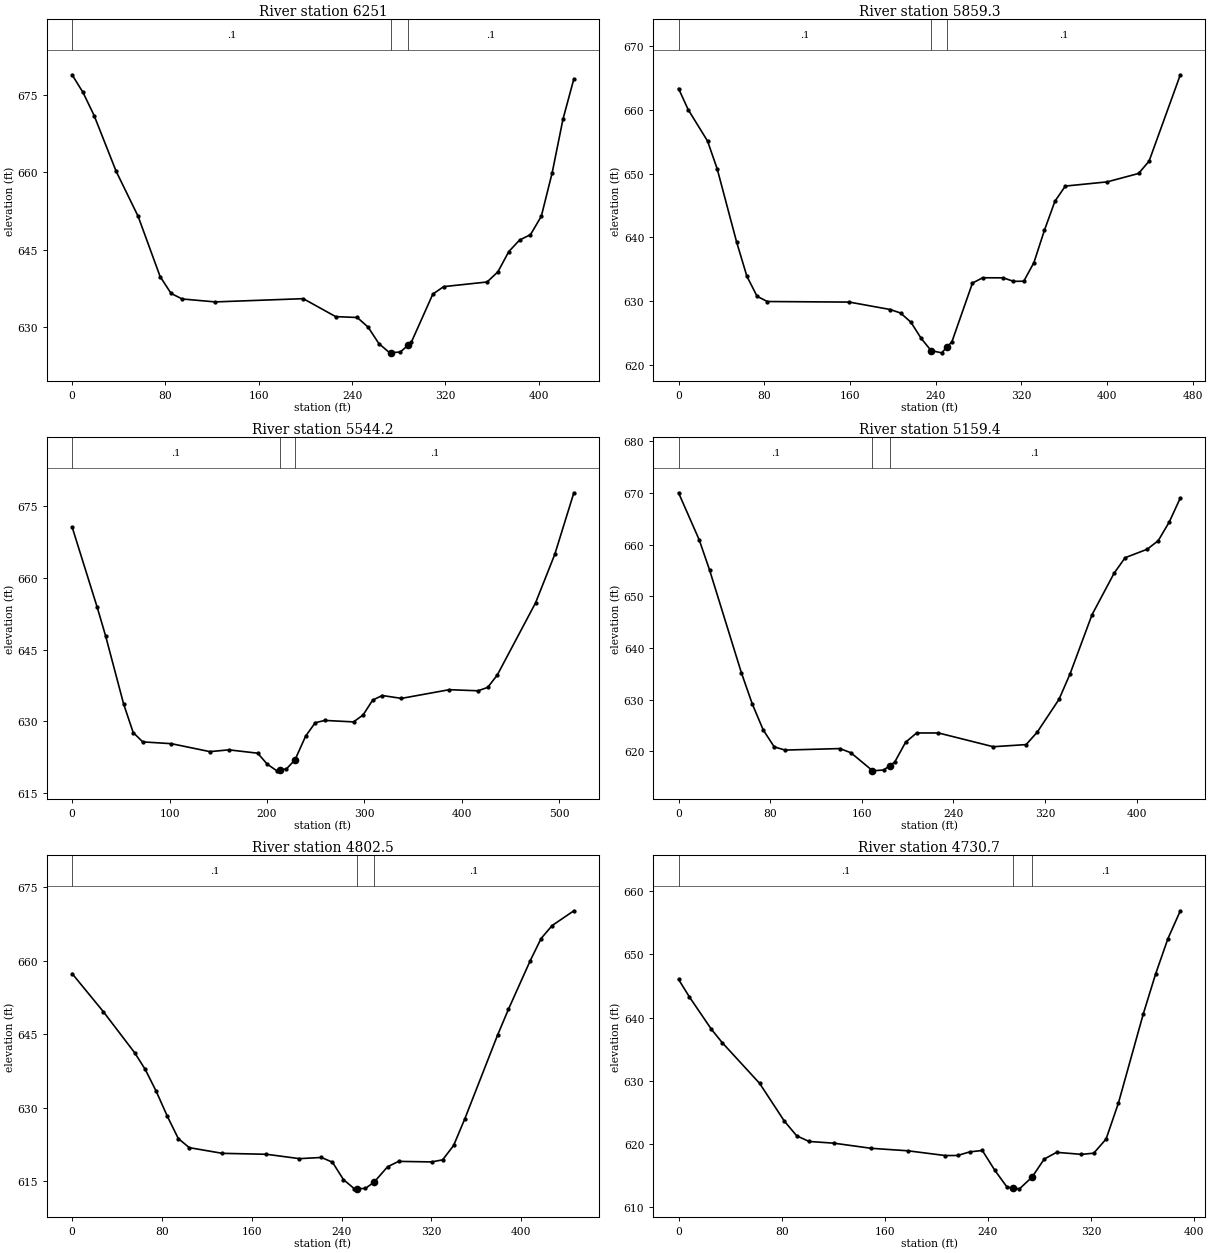
Type RM Length L Ch R = 1 ,6251    ,387.5,391.8,395.9
XS GIS Cut Line= 4
     1826650.595      431401.124     1826811.185      431517.227
     1826897.991      431586.671     1826994.562      431659.371
#Sta/Elev= 30
       0  678.98     9.4  675.54    18.9  671.06    37.8  660.21    56.6  651.48
    75.5  639.75    84.9  636.48    94.4   635.4   122.7  634.83   198.2  635.46
     226  631.97   244.5   631.8   253.8  629.93     263  626.74   272.3  624.93
   273.4  624.95   281.5   625.1   288.4  626.48   290.8  626.96   309.3  636.35
   318.6   637.8   355.8   638.7   365.1  640.68   374.4  644.61   383.7  646.86
     393   647.9   402.3  651.48   411.6  659.92   420.9  670.38   430.2  678.18
#Mann= 3 , 0 , 0
       0      .1       0   273.4    .045       0   288.4      .1       0
Bank Sta=273.4,288.4
XS Rating Curve= 0 ,0
Exp/Cntr=0.3,0.1

Type RM Length L Ch R = 1 ,5859.3  ,315.5,315.1,314.7
XS GIS Cut Line= 4
     1826470.473      431676.732      1826499.77      431722.305
     1826680.977      431932.808     1826781.888      432025.039
#Sta/Elev= 30
       0  663.38       9  660.07    27.1  655.13    36.1  650.76    54.2   639.3
    63.8  633.91    73.3  630.76    82.9  629.93   159.5  629.84   197.8  628.67
   207.4  628.12     217  626.68   226.6  624.14   235.8  622.23   245.7  621.87
   250.8  622.79   255.3  623.61   274.5  632.83     284  633.66   303.2  633.65
   312.8   633.1   322.4  633.12   331.9  636.05   341.7  641.13   351.5  645.68
   361.2  648.06   400.3  648.72   429.6  650.04   439.4  651.97   468.6  665.54
#Mann= 3 , 0 , 0
       0      .1       0   235.8    .045       0   250.8      .1       0
Bank Sta=235.8,250.8
XS Rating Curve= 0 ,0
Exp/Cntr=0.3,0.1

Type RM Length L Ch R = 1 ,5544.2  ,381.7,384.8,388.5
XS GIS Cut Line= 3
     1826250.204      431933.893     1826286.011      431957.765
     1826599.597      432310.413
#Sta/Elev= 30
       0  670.69    25.8  653.86    34.4  647.88    52.9  633.63    62.7  627.66
    72.5   625.7     102  625.32   141.4  623.66     161  624.03   190.5  623.33
   200.3  621.03   210.2  619.64   213.7  619.79     220  620.06   228.7  621.92
   239.7  626.91   249.5   629.7   259.3  630.19   288.8  629.88   298.6  631.32
   308.5  634.45   318.3   635.4     338   634.8   387.1  636.62   416.6  636.39
   426.5   637.1   436.3  639.68   475.6  654.79   495.3  664.92   514.9  677.82
#Mann= 3 , 0 , 0
       0      .1       0   213.7    .045       0   228.7      .1       0
Bank Sta=213.7,228.7
XS Rating Curve= 0 ,0
Exp/Cntr=0.3,0.1

Type RM Length L Ch R = 1 ,5159.4  ,355.2,356.9,357.5
XS GIS Cut Line= 4
     1826029.935      432205.161     1826052.722      432244.223
     1826214.397      432492.704     1826251.289       432581.68
#Sta/Elev= 30
       0  670.04    18.1   660.9    27.1  655.08    54.8  635.24    64.4  629.14
    73.9  624.14    83.5  620.85      93  620.23   140.8  620.52   150.4  619.72
   169.2  616.26   169.5  616.21   179.1  616.38   184.2  617.19   188.7   617.9
   198.2  621.75   207.8  623.54   226.9  623.54   274.7  620.88   303.4  621.29
     313  623.67   332.1  630.05   341.7  634.95   360.9  646.42   380.2  654.47
   389.8  657.47   409.1  659.11   418.7  660.76   428.4  664.41     438  669.04
#Mann= 3 , 0 , 0
       0      .1       0   169.2    .045       0   184.2      .1       0
Bank Sta=169.2,184.2
XS Rating Curve= 0 ,0
Exp/Cntr=0.3,0.1

Type RM Length L Ch R = 1 ,4802.5  ,72.2,71.8,71.5
XS GIS Cut Line= 4
     1825742.392      432363.581     1825763.008       432425.43
     1825911.662      432679.336     1825946.385      432759.631
#Sta/Elev= 30
       0  657.39    27.9   649.6    55.9  641.19    65.2  637.82      75  633.35
    84.8   628.3    94.6  623.74   104.4  621.88   133.8  620.72   173.1  620.53
   202.5  619.64   222.1  619.88   231.9  618.91   241.7  615.36   251.5  613.48
     254   613.5   261.3  613.57     269  614.85     281  617.98   290.8  619.08
   320.2  618.97     330  619.39   339.8  622.32   349.6  627.66   378.9   644.8
   388.6  650.08     408  659.99   417.7  664.53   427.5  667.17   446.9  670.19
#Mann= 3 , 0 , 0
       0      .1       0     254    .045       0     269      .1       0
Bank Sta=254,269
XS Rating Curve= 0 ,0
Exp/Cntr=0.3,0.1

Type RM Length L Ch R = 1 ,4730.7  ,56.2,56.1,56.2
XS GIS Cut Line= 3
     1825678.373      432413.494     1825691.393      432444.961
     1825873.685      432749.866
#Sta/Elev= 30
       0  646.04     8.5  643.24    25.5  638.14      34     636    62.9  629.58
    82.1   623.6    91.7  621.27   101.3  620.38   120.5  620.11   149.3   619.3
   178.1   618.9   206.9  618.15   216.5  618.16   226.1  618.74   235.7  618.95
   245.3  615.84   254.9  613.14   259.2  613.02   264.5  612.88   274.2  614.72
   283.7  617.59   293.3  618.66   312.5  618.34   322.1  618.52   331.7  620.76
   341.3  626.48   360.5  640.53   370.1  646.88   379.7   652.5   389.3   656.9
#Mann= 3 , 0 , 0
       0      .1       0   259.2    .045       0   274.2      .1       0
Bank Sta=259.2,274.2
XS Rating Curve= 0 ,0
Exp/Cntr=0.3,0.1

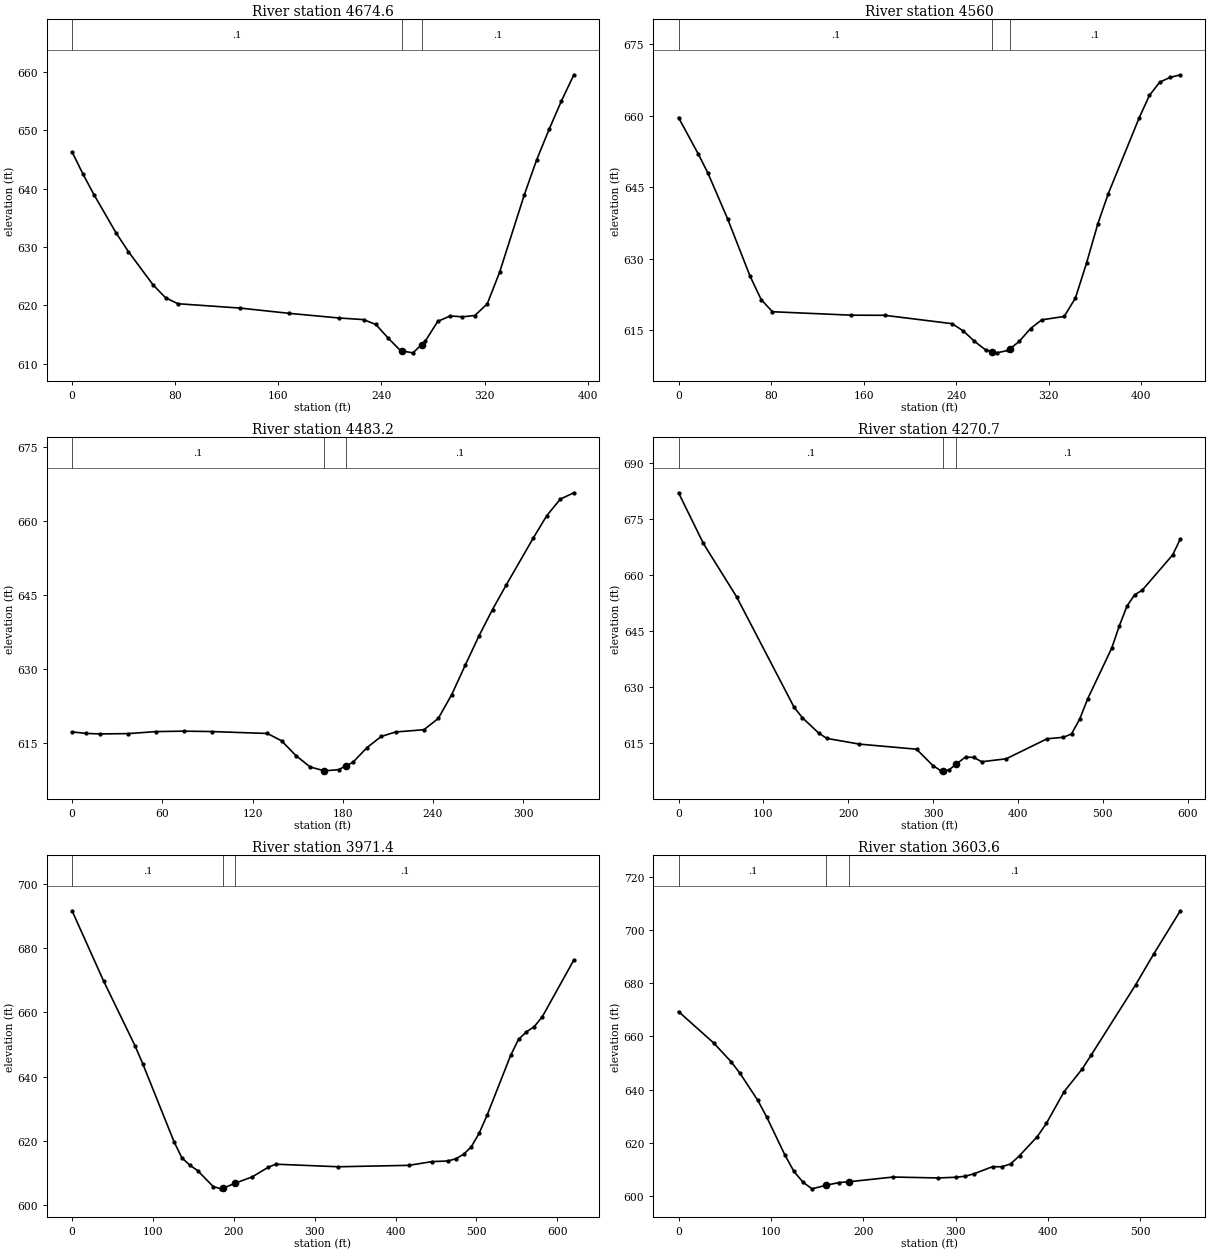
Type RM Length L Ch R = 1 ,4674.6  ,116.6,114.5,111.9
XS GIS Cut Line= 3
     1825633.885      432448.216     1825646.906      432479.683
     1825829.197      432784.588
#Sta/Elev= 30
       0  646.29     8.5  642.48      17  638.96      34  632.46    43.7   629.2
    62.9  623.48    72.5  621.29    82.1  620.26   130.1  619.52   168.5  618.61
   206.9  617.82   226.1  617.54   235.7   616.7   245.3  614.35   254.9   612.2
   256.2  612.15   264.5  611.84   271.2  613.26   274.1  613.88   283.7  617.23
   293.3  618.16   302.9  618.02   312.5  618.24   322.1  620.24   331.7  625.66
   350.9  638.97   360.5  644.97   370.1  650.17   379.7  655.05   389.3  659.52
#Mann= 3 , 0 , 0
       0      .1       0   256.2    .045       0   271.2      .1       0
Bank Sta=256.2,271.2
XS Rating Curve= 0 ,0
Exp/Cntr=0.3,0.1

Type RM Length L Ch R = 1 ,4560    ,77.6,76.9,76.1
XS GIS Cut Line= 4
     1825493.911      432522.001     1825526.463      432549.128
      1825718.52      432805.204     1825752.157      432868.138
#Sta/Elev= 30
       0  659.56      17  651.96    25.4  647.92    42.4  638.35    61.8  626.33
    71.5  621.37    81.2  618.85   149.1  618.13   178.2   618.1   236.4  616.35
   246.1  614.84   255.8  612.66   265.5  610.83   271.3  610.47   275.2  610.23
   284.9  610.74   286.3  611.02   294.6  612.65   304.3  615.32     314  617.15
   333.4  617.86   343.1  621.72   352.8  629.12   362.5   637.3   371.4  643.54
   398.2   659.5   407.1  664.22     416  666.99   424.9  667.98   433.8  668.54
#Mann= 3 , 0 , 0
       0      .1       0   271.3    .045       0   286.3      .1       0
Bank Sta=271.3,286.3
XS Rating Curve= 0 ,0
Exp/Cntr=0.3,0.1

Type RM Length L Ch R = 1 ,4483.2  ,212.1,212.5,213.1
XS GIS Cut Line= 4
     1825495.068      432641.489     1825574.929       432743.92
      1825646.11      432832.461     1825691.249      432910.586
#Sta/Elev= 30
       0  617.28     9.3  616.97    18.6  616.87    37.1  616.93    55.7  617.34
    74.2  617.43    92.8  617.35   129.9  616.96   139.4  615.46   148.8   612.5
   158.3  610.19   167.4  609.43   167.8   609.4   177.2  609.64   182.4  610.44
   186.7  611.11   196.2  614.12   205.6  616.35   215.1  617.26     234  617.72
   243.5  619.99   252.5  624.84   261.5  630.81   270.6   636.7   279.6  642.04
   288.6  646.94   306.6  656.45   315.7  661.04   324.7  664.38   333.7  665.66
#Mann= 3 , 0 , 0
       0      .1       0   167.4    .045       0   182.4      .1       0
Bank Sta=167.4,182.4
XS Rating Curve= 0 ,0
Exp/Cntr=0.3,0.1

Type RM Length L Ch R = 1 ,4270.7  ,303.2,299.3,295.2
XS GIS Cut Line= 4
      1825259.97       432600.56     1825286.011      432704.727
     1825523.859      433018.963     1825589.831      433079.727
#Sta/Elev= 30
       0  682.08    29.3  668.49    68.3  654.24   136.2  624.58   145.8  621.83
     165   617.7   174.7  616.26   213.1  614.72   280.4  613.36   299.6  608.99
   309.2  607.56   311.6  607.62   318.8  607.82   326.6  609.28   338.1  611.25
   347.7  611.16   357.3     610   386.1  610.79   434.2  616.15   453.4  616.55
     463  617.45   472.6  621.41   482.2  626.94   510.4  640.46   519.4  646.47
   528.4  651.74   537.4  654.74   546.3  655.97   582.2  665.44   591.2  669.69
#Mann= 3 , 0 , 0
       0      .1       0   311.6    .045       0   326.6      .1       0
Bank Sta=311.6,326.6
XS Rating Curve= 0 ,0
Exp/Cntr=0.3,0.1

Type RM Length L Ch R = 1 ,3971.4  ,370.3,367.8,365.9
XS GIS Cut Line= 4
     1824996.081      432864.449     1825056.845       432913.06
      1825384.97      433213.407     1825438.789      433295.005
#Sta/Elev= 30
       0  691.63    38.9  669.83    77.8  649.65    87.5  643.96   126.2   619.7
   135.8  614.77   145.5   612.5   155.2   610.8   174.5  605.84   184.2  605.12
   186.5  605.28   201.5  606.87   222.9  608.85   242.2  611.79   251.9  612.79
   329.2  611.99   416.3  612.43   445.3   613.6   464.6  613.78   474.3  614.47
     484  615.84   493.6   618.2   503.3  622.42     513  627.96   542.2  646.61
     552  651.64   561.8  653.96   571.5  655.62   581.3  658.63   620.4  676.33
#Mann= 3 , 0 , 0
       0      .1       0   186.5    .045       0   201.5      .1       0
Bank Sta=186.5,201.5
XS Rating Curve= 0 ,0
Exp/Cntr=0.3,0.1

Type RM Length L Ch R = 1 ,3603.6  ,90.7,92,92.4
XS GIS Cut Line= 4
     1824871.081      433192.574     1824914.484      433255.074
     1825144.468      433420.865     1825250.718      433570.865
#Sta/Elev= 30
       0  669.33      38  657.57    57.1  650.44    66.6  646.14    85.9  635.98
    95.6  629.68   115.2   615.5     125  609.34   134.8   605.3   144.5  602.82
     160 604.192   173.9  605.18     185 605.496   232.5  607.25   281.4   606.9
     301  607.18   310.7  607.57   320.5  608.54     340  611.13   349.8   611.1
   359.6  612.15   369.3  615.28   388.6  622.45   398.3  627.35   417.6  639.32
     437  647.72   446.7  652.91     495  679.36   514.4  690.83   543.4  707.14
#Mann= 3 , 0 , 0
       0      .1       0     160    .045       0     185      .1       0
Bank Sta=160,185
XS Rating Curve= 0 ,0
Exp/Cntr=0.3,0.1

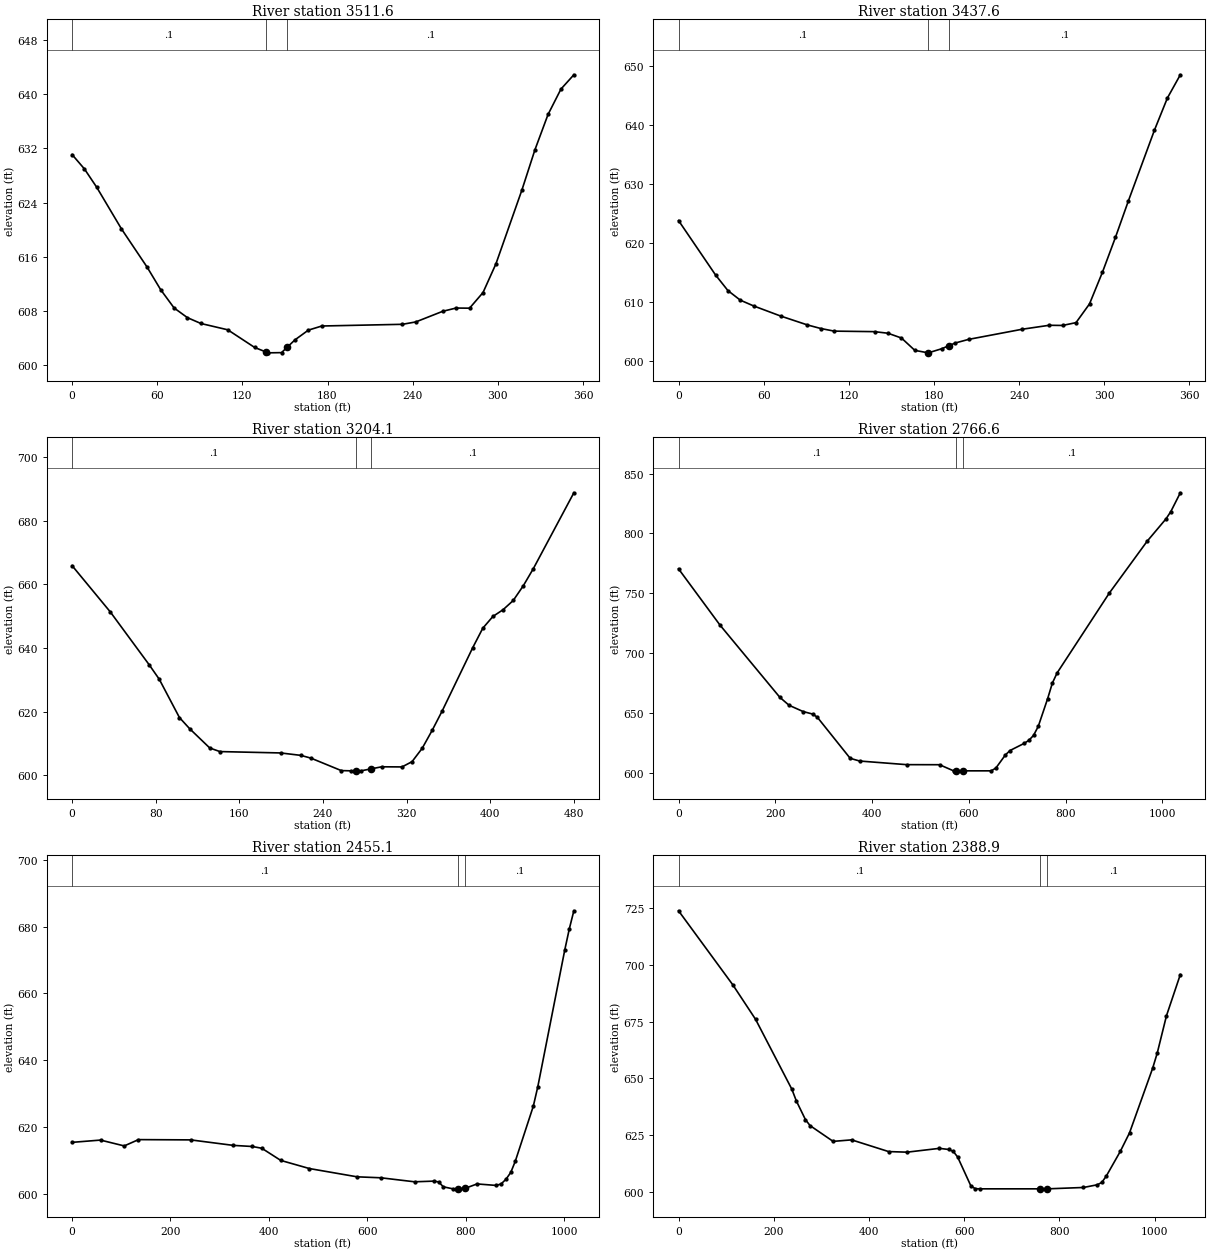
Type RM Length L Ch R = 1 ,3511.6  ,73.1,74,75.5
XS GIS Cut Line= 4
      1824889.65      433301.595      1824896.16      433344.563
     1825095.379      433489.095     1825134.442      433539.876
#Sta/Elev= 30
       0  631.08     8.7  628.96    17.4  626.24    34.8  620.11    52.9  614.46
    62.4  611.15    71.9  608.44    81.3  607.01    90.8  606.15   109.7  605.22
   128.7  602.61   136.6  601.95   138.1  601.82   147.6  601.85   151.6  602.65
   157.1  603.74   166.5  605.17     176  605.78   232.8  606.03   242.2  606.38
   261.2  607.95   270.6  608.43   280.1  608.41   289.6  610.72   298.7  614.96
     317  625.85   326.2   631.8   335.4  636.99   344.5  640.74   353.6  642.85
#Mann= 3 , 0 , 0
       0      .1       0   136.6    .045       0   151.6      .1       0
Bank Sta=136.6,151.6
XS Rating Curve= 0 ,0
Exp/Cntr=0.3,0.1

Type RM Length L Ch R = 1 ,3437.6  ,232.6,233.5,232.9
XS GIS Cut Line= 4
     1824853.192      433352.376     1824859.702      433395.345
     1825058.921      433539.876     1825097.983      433590.657
#Sta/Elev= 30
       0  623.86    26.1  614.63    34.8  611.99    43.5  610.37    52.9  609.39
    71.9  607.68    90.8  606.17   100.3  605.56   109.7  605.12   138.1  605.03
   147.6  604.76   157.1  603.95   166.5  601.86   175.7  601.45     176  601.44
   185.4  602.13   190.7  602.67   194.9   603.1   204.4  603.72   242.2  605.44
   261.2  606.11   270.6  606.08   280.1  606.56   289.6  609.73   298.7  615.09
   307.9  621.02     317  627.19   335.4   639.2   344.5  644.63   353.6  648.56
#Mann= 3 , 0 , 0
       0      .1       0   175.7    .045       0   190.7      .1       0
Bank Sta=175.7,190.7
XS Rating Curve= 0 ,0
Exp/Cntr=0.3,0.1

Type RM Length L Ch R = 1 ,3204.1  ,439.5,437.5,434.2
XS GIS Cut Line= 3
     1824680.109      433501.602      1824728.72      433543.268
     1825042.956      433815.838
#Sta/Elev= 30
       0  665.85    36.6   651.3    73.7  634.74    83.4  630.17   102.7  618.14
   112.4  614.66   131.7  608.58   141.4  607.45   199.5  607.02   218.8  606.26
   228.5  605.39   257.5  601.48   267.2   601.4   271.2  601.41   276.8  601.43
   286.2  602.03   296.2  602.67   315.6  602.63   325.2  604.28   334.9  608.47
   344.6   614.2   354.2  620.31   383.3  640.11   392.9   646.2   402.6   649.9
   412.3  652.01     422   654.9   431.6  659.51   441.3  664.94     480  688.73
#Mann= 3 , 0 , 0
       0      .1       0   271.2    .045       0   286.2      .1       0
Bank Sta=271.2,286.2
XS Rating Curve= 0 ,0
Exp/Cntr=0.3,0.1

Type RM Length L Ch R = 1 ,2766.6  ,326.8,311.5,296.3
XS GIS Cut Line= 4
     1824248.106      433679.553     1824383.523      433863.581
      1824831.44      434155.248     1825105.745      434151.775
#Sta/Elev= 30
       0  770.36    85.7  723.31   209.4   662.9   228.5  656.23   257.6  650.99
   277.1   648.9   286.8  646.29   354.8  611.88   374.3  609.61   471.4  606.58
   539.5  606.52   568.6   601.4   572.7   601.4   587.7   601.4   646.4   601.4
   656.1  603.78   675.5  614.61   685.2  618.39   714.4  624.35   724.1  626.88
   733.8     631   743.6  638.56     763  661.76   772.8  674.84   782.6   683.3
   890.4  750.04   968.7  793.45  1007.9  812.27  1017.7   818.3  1037.3  833.98
#Mann= 3 , 0 , 0
       0      .1       0   572.7    .045       0   587.7      .1       0
Bank Sta=572.7,587.7
XS Rating Curve= 0 ,0
Exp/Cntr=0.3,0.1

Type RM Length L Ch R = 1 ,2455.1  ,65.2,66.2,67.1
XS GIS Cut Line= 5
     1823912.169      434256.145     1824313.211      434394.165
     1824544.981      434373.332     1824779.356      434360.311
     1824896.544      434308.228
#Sta/Elev= 30
       0  615.33    57.8  616.01     106  614.26     135  616.15     241  616.07
   327.7  614.42   366.3  614.09   385.6  613.56   424.1  609.92   482.3  607.48
   579.3     605   627.7  604.71     696  603.51   735.1  603.71   744.9  603.48
   754.6     602   774.2   601.4   784.3   601.4   799.3  601.58   823.1  602.87
   862.2  602.42     872  602.88   881.8  604.26   891.6  606.32   900.7  609.64
   937.4  626.17   946.5  631.98  1001.5  673.11  1010.6  679.33  1019.8  684.72
#Mann= 3 , 0 , 0
       0      .1       0   784.3    .045       0   799.3      .1       0
Bank Sta=784.3,799.3
XS Rating Curve= 0 ,0
Exp/Cntr=0.3,0.1

Type RM Length L Ch R = 1 ,2388.9  ,88.4,80.6,72
XS GIS Cut Line= 6
     1823992.898       434709.27     1824214.252      434560.832
      1824518.94      434500.936      1824581.44      434433.228
     1824781.961      434430.624     1824951.231      434357.707
#Sta/Elev= 30
       0  723.86   114.2  691.19   161.8  676.06     238  645.28   247.5   640.1
   266.5  631.91   276.2  629.26   324.7   622.3   363.6  622.97   441.2  617.81
     480  617.55   547.9  619.23   567.3  618.74     577   617.9   586.2  615.44
   613.9  602.76   623.1  601.46   632.3   601.4   759.7   601.4   774.7   601.4
   850.6     602   879.4  603.18   889.1  604.22   898.8  607.14   927.9  617.89
   947.3  626.06   995.8  654.47  1005.5  661.18  1024.9  677.64    1054  695.78
#Mann= 3 , 0 , 0
       0      .1       0   759.7    .045       0   774.7      .1       0
Bank Sta=759.7,774.7
XS Rating Curve= 0 ,0
Exp/Cntr=0.3,0.1

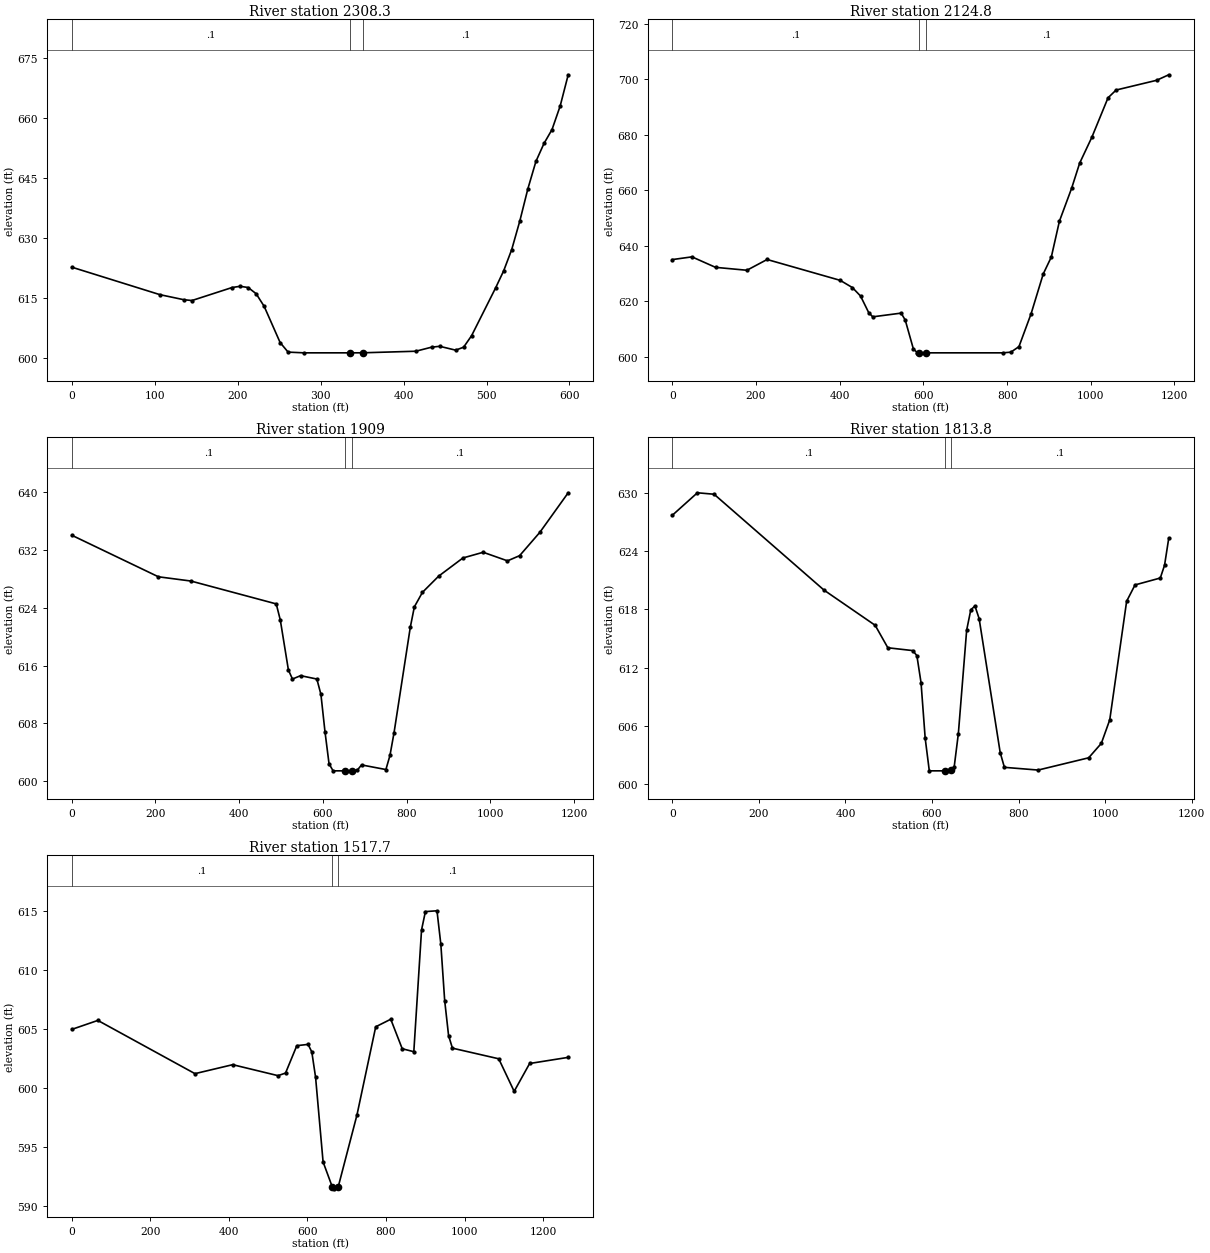
Type RM Length L Ch R = 1 ,2308.3  ,185.6,183.5,182.3
XS GIS Cut Line= 4
     1824446.023      434724.895     1824607.481      434545.207
     1824849.669      434451.457     1824940.815      434417.603
#Sta/Elev= 30
       0   622.8   106.3  615.93   135.3  614.66   144.9  614.47   193.3  617.72
   202.9  618.02   212.6  617.72   222.2  616.18   231.9  613.03   251.2  603.96
   260.8  601.58     280   601.4   335.6   601.4   350.6  601.41   414.7   601.8
   433.9  602.82   443.6  603.03   462.8  602.07   472.4  602.81     482  605.68
     511  617.63   520.7  621.89   530.4   627.2   540.2  634.37   549.9   642.4
   559.6  649.23   569.3   653.7     579  657.18   588.8  663.05   598.5  670.86
#Mann= 3 , 0 , 0
       0      .1       0   335.6    .045       0   350.6      .1       0
Bank Sta=335.6,350.6
XS Rating Curve= 0 ,0
Exp/Cntr=0.3,0.1

Type RM Length L Ch R = 1 ,2124.8  ,214.6,215.9,215.7
XS GIS Cut Line= 4
     1824190.815      434976.428     1824336.648      434858.373
     1824913.037      434601.428     1825274.148      434531.984
#Sta/Elev= 30
       0  635.02    46.9     636   103.2  632.22   178.2  631.17   226.5  635.05
   401.2  627.53   430.4  624.92   449.8  621.88   469.2  615.93   478.9  614.38
   546.8  615.72   556.6  613.22     576  602.85   585.7   601.4   590.3   601.4
   605.3   601.4   789.6   601.4     809  601.64   828.4  603.64   857.4  615.48
   886.4  629.83   905.8  635.96   925.1  648.86   954.2  660.69   973.5  669.79
  1002.6  679.11  1041.3  693.34  1060.6  696.14  1157.4  699.65  1186.4  701.64
#Mann= 3 , 0 , 0
       0      .1       0   590.3    .045       0   605.3      .1       0
Bank Sta=590.3,605.3
XS Rating Curve= 0 ,0
Exp/Cntr=0.3,0.1

Type RM Length L Ch R = 1 ,1909    ,96,95.1,94.3
XS GIS Cut Line= 4
     1824234.217       435189.97     1824380.051      435071.914
      1824956.44       434814.97     1825317.551      434745.525
#Sta/Elev= 30
       0  634.07     207  628.31   284.7  627.72   488.6  624.55   498.3  622.32
   517.7  615.38   527.4  614.13   546.8   614.6   585.7  614.13   595.4     612
   605.1  606.83   614.8  602.38   624.5   601.4   654.1   601.4   669.1   601.4
   682.8  601.53   692.5  602.22   750.7  601.58   760.4  603.53   770.2   606.7
     809  621.31   818.7  624.14     838  626.15   876.8   628.4   934.8  630.92
   983.2  631.71  1041.3  630.52  1070.3  631.24  1118.7  634.48  1186.4  639.96
#Mann= 3 , 0 , 0
       0      .1       0   654.1    .045       0   669.1      .1       0
Bank Sta=654.1,669.1
XS Rating Curve= 0 ,0
Exp/Cntr=0.3,0.1

Type RM Length L Ch R = 1 ,1813.8  ,274.7,296.1,317.6
XS GIS Cut Line= 5
     1824272.412      435183.025     1824418.245      435071.914
     1824720.329      435030.248     1824918.245      434933.025
     1825334.912      434797.609
#Sta/Elev= 30
       0  627.67    57.9  629.98    96.5  629.83   350.6  619.97   468.6  616.36
   497.9  614.05   555.4  613.76     565  613.24   574.6  610.46   584.2  604.74
   593.7   601.4   629.6   601.4   644.6  601.53   651.3  601.84   660.8  605.22
     680  615.86   689.6  617.96   699.2  618.34   708.8  617.05   757.5  603.27
   767.2  601.76   845.1  601.48   961.9  602.74   991.1  604.22  1010.6  606.64
  1049.6  618.83    1069  620.51  1127.4  621.22  1137.2  622.53  1146.9  625.31
#Mann= 3 , 0 , 0
       0      .1       0   629.6    .045       0   644.6      .1       0
Bank Sta=629.6,644.6
XS Rating Curve= 0 ,0
Exp/Cntr=0.3,0.1

Type RM Length L Ch R = 1 ,1517.7  ,1543,1517.7,1501.4
XS GIS Cut Line= 5
     1824276.752      435360.977     1824502.447      435289.362
     1824775.884      435198.216     1825049.322      435313.234
     1825311.908      434957.331
#Sta/Elev= 30
       0  604.97    66.3  605.73   313.6  601.22   409.7  601.98     525  601.05
   544.2  601.27   572.9  603.59   601.6   603.7   611.1  603.06   620.7  600.91
   639.8  593.74   663.5   591.6   668.6  591.46   678.5  591.65     726  597.71
   773.8  605.19   812.1  605.83   841.3  603.33   870.8  603.08   890.5   613.4
   900.3  614.95   929.8  615.02   939.6  612.19   949.4  607.41   959.3  604.45
   969.1  603.38    1087  602.48  1126.3  599.72  1165.7  602.08  1263.9   602.6
#Mann= 3 , 0 , 0
       0      .1       0   663.5    .045       0   678.5      .1       0
Bank Sta=663.5,678.5
XS Rating Curve= 0 ,0
Exp/Cntr=0.3,0.1

Chan Stop Cuts=-1
Use User Specified Reach Order=0
Composite Channel Slope=5